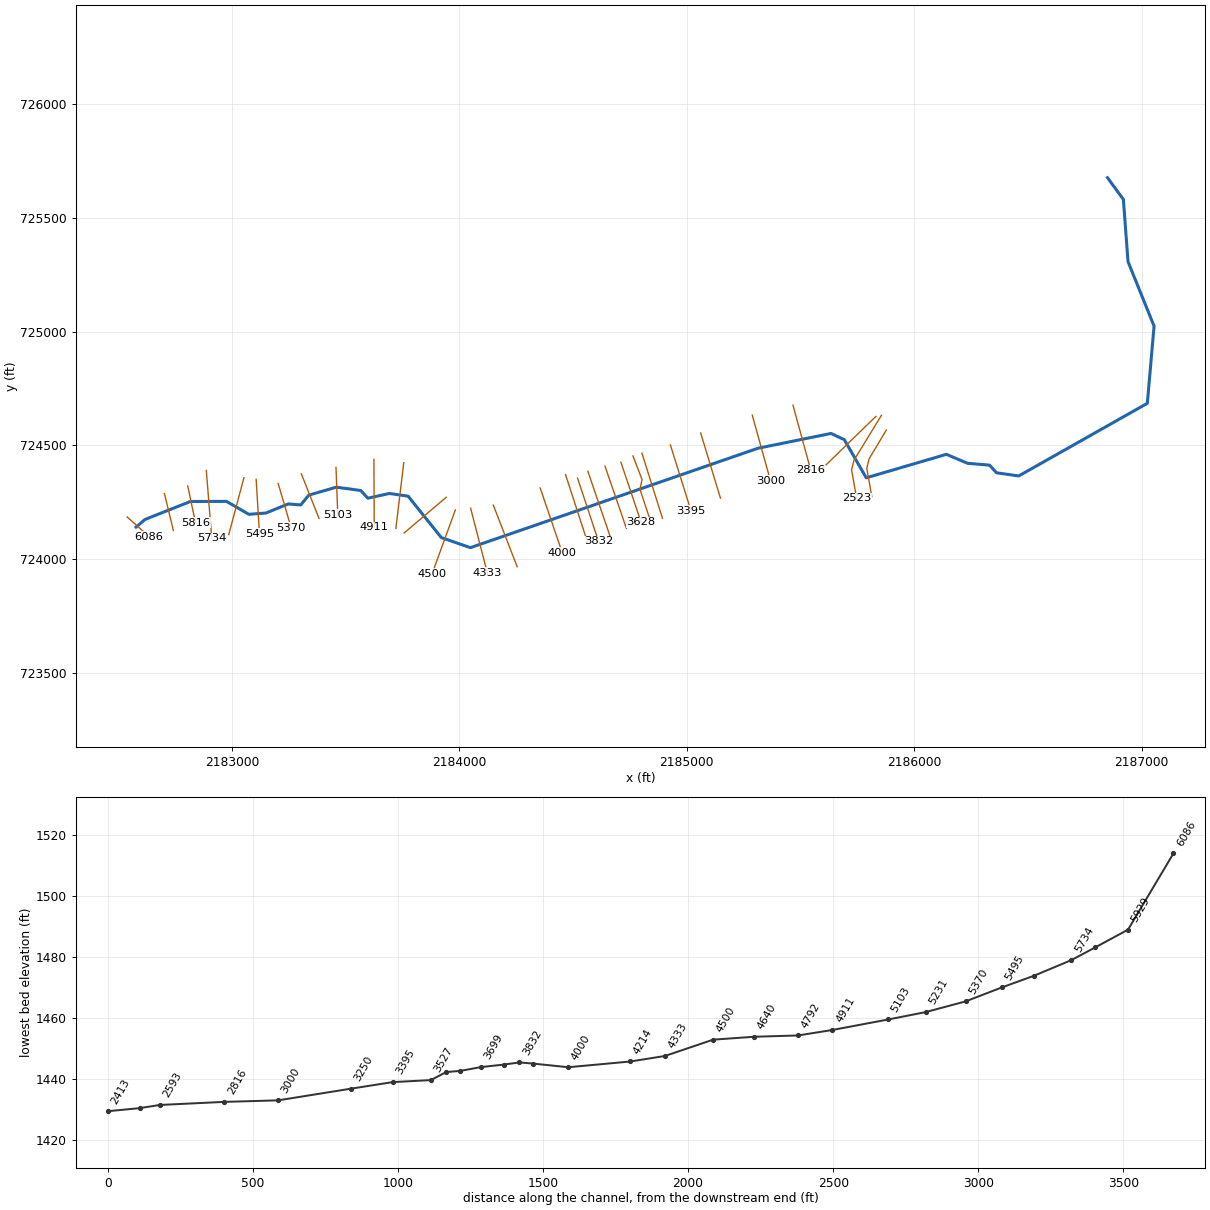
--- JAWBNRN.prj (project) ---

Proj Title=JAWBNRN
Current Plan=p01
Default Exp/Contr=0.3,0.1
English Units
Geom File=g01
Flow File=f01
Plan File=p01
Y Axis Title=Elevation
X Axis Title(PF)=Main Channel Distance
X Axis Title(XS)=Station
BEGIN DESCRIPTION:
---------- MODELED AS PART OF WVEMD CTP PROGRAM, 2023----------
Stream Name: Jawbone Run
Flood Zone:  AFH
Upshur County, WV
HEC-RAS Version: RAS 6.3
Vertical Datum: NAVD88
Projection: NAD 1983 StatePlane West Virginia S FIPS 4702 (US Feet)
Terrain: 1-meter LIDAR (FEMA Region III 3DEP collected 2016-2018)
Land Use: 2019 NLCD
Hydrologic Method:
WV SIR2010-5033 regression equations
Additional Model Notes:
None
END DESCRIPTION:
DSS Export Rating Curves= 0
DSS Export Rating Curve Sorted= 0
DSS Export Volume Flow Curves= 0
DXF OffsetX= 0
DXF OffsetY= 0
DXF ScaleX= 1
DXF ScaleY= 10

--- JAWBNRN.p01 (plan) ---

Plan Title=Floodplain
Program Version=6.31
Short Identifier=Floodplain
Geom File=g01
Flow File=f01
Subcritical Flow
K Sum by GR= 0
Std Step Tol= 0.01
Critical Tol= 0.01
Num of Std Step Trials= 20
Max Error Tol= 0.3
Flow Tol Ratio= 0.001
Split Flow NTrial= 30
Split Flow Tol= 0.02
Split Flow Ratio= 0.02
Log Output Level= 0
Friction Slope Method= 1
Unsteady Friction Slope Method= 2
Unsteady Bridges Friction Slope Method= 1
Parabolic Critical Depth
Global Vel Dist= 0 , 0 , 0
Global Log Level= 0
CheckData=True
Encroach Param=-1 ,0,0, 0
Computation Interval=1MIN
Output Interval=1HOUR
Instantaneous Interval=1HOUR
Mapping Interval=1HOUR
Computation Time Step Use Courant=        0
Computation Time Step Use Time Series=    0
Computation Time Step Count To Double=0
Computation Time Step Max Doubling=0
Computation Time Step Max Halving=0
Computation Time Step Residence Courant=0
Run HTab= 0
Run UNet= 0
Run Sediment= 0
Run PostProcess= 0
Run WQNet= 0
Run RASMapper=-1
UNET Theta= 1
UNET Theta Warmup= 1
UNET ZTol= 0.02
UNET ZSATol= 0.02
UNET MxIter= 20
UNET Max Iter WO Improvement= 0
UNET MaxInSteps= 0
UNET DtIC= 0
UNET DtMin= 0
UNET MaxCRTS= 20
UNET WFStab= 2
UNET SFStab= 1
UNET WFX= 1
UNET SFX= 1
UNET Gravity=32.17405
UNET 1D Methodology=Finite Difference
UNET DSS MLevel= 4
UNET Pardiso=0
UNET DZMax Abort= 100
UNET Use Existing IB Tables=-1
UNET Froude Reduction=False
UNET Froude Limit= 0.8
UNET Froude Power= 4
UNET D1 Cores= 0
UNET WindReference=Eulerian
UNET WindDragFormulation=Hsu (1988)
UNET D2 Coriolis=0
UNET D2 Cores= 0
UNET D2 Theta= 1
UNET D2 Theta Warmup= 1
UNET D2 Z Tol= 0.01
UNET D2 Volume Tol= 0.01
UNET D2 Max Iterations= 20
UNET D2 Equation= 0
UNET D2 RampUpFraction=0.1
UNET D2 TimeSlices= 1
UNET D2 Turbulence Formulation=None
UNET D2 Eddy Viscosity=0.3
UNET D2 Transverse Eddy Viscosity=0.1
UNET D2 Smagorinsky Mixing=0.05
UNET D2 BCVolumeCheck=0
UNET D2 Cores=0
UNET D2 SolverType=PARDISO (Direct)
UNET D2 Minimum Iterations= 3
UNET D2 Maximum Iterations= 30
UNET D2 Restart Number= 10
UNET D2 Relaxation Coeff=1.3
UNET D2 SOR Precondition Iterations= 10
UNET D2 ILUT Maximum Fill= 8
UNET D2 ILUT Tolerance=1E-08
UNET D2 Convergence Tolerance=0.00001
UNET D1D2 MaxIter= 0
UNET D1D2 ZTol=0.01
UNET D1D2 QTol=0.1
UNET D1D2 MinQTol=1
Write IC File= 0
Write IC File at Fixed DateTime=0
Write IC File at Sim End=0
Echo Input=False
Echo Parameters=False
Echo Output=False
Write Detailed= 0
HDF Write Warmup=0
HDF Write Time Slices=0
HDF Flush=0
HDF Compression= 1
HDF Chunk Size= 1
HDF Spatial Parts= 1
HDF Use Max Rows=0
HDF Fixed Rows= 1
Calibration Method= 0
Calibration Iterations= 20
Calibration Max Change=0.05
Calibration Tolerance=0.2
Calibration Maximum=1.5
Calibration Minimum=0.5
Calibration Optimization Method= 1
WQ AD Non Conservative
WQ ULTIMATE=-1
WQ Max Comp Step=1HOUR
WQ Output Interval=15MIN
WQ Output Selected Increments= 0
WQ Create Restart=0
WQ Fixed Restart=0
WQ System Summary=0
WQ Write To DSS=0
Sorting and Armoring Iterations= 10
XS Update Threshold= 0.02
Bed Roughness Predictor= 0
Hydraulics Update Threshold= 0.02
Energy Slope Method= 1
Volume Change Method= 1
Sediment Retention Method= 0
Sediment TS Multiplier= 1
Warm Up Method= 0
XS Weighting Method= 0
Number of US Weighted Cross Sections= 1
Number of DS Weighted Cross Sections= 1
Upstream XS Weight=0
Main XS Weight=1
Downstream XS Weight=0
Number of DS XS's Weighted with US Boundary= 1
Upstream Boundary Weight= 1
Weight of XSs Associated with US Boundary= 0
Number of US XS's Weighted with DS Boundary= 1
Downstream Boundary Weight= 0.5
Weight of XSs Associated with DS Boundary= 0.5
Percentile Method= 0
Sediment Output Level= 3
Mass or Volume Output= 0
Output Increment Type= 1
Profile and TS Output Increment= 1
Transport Output Increment 1
XS Output Flag= 0
XS Output Increment= 10
Read HDF5 Sediment Hotstart= 0
Sediment Hotstart Type= 0
Write Gradation File= 0
Read Gradation Hotstart= 0
Write HDF5 File= 1
Write Binary Output= 1
Write DSS Sediment File= 0
DSS Sediment Output Type= 1
SV Curve= 0
Specific Gage Flag= 0
Subcell Erosion Methods= 0
Subcell Deposition Methods= 0
Advection Scheme= 1
Matrix Solver= 0
Implicit Weighting Factor= 1
Maximum Outer Loop Convergence Iterations= 5
Convergence Maximum Absolute= 0.001
Convergence RMSE= 0.0001
Grain Fractions Max Abs Error= 0.001
Max Subgrid Regions= 1
Max Subgrid Length Scale= 3.402823E+38
Initial Layer Thickness= 3.402823E+38
Min Layer Thickness= 3.402823E+38
Max Layer Thickness= 3.402823E+38
Number of Layers= 5

--- JAWBNRN.f01 (steady flow) ---

Flow Title=Flow
Program Version=6.31
Number of Profiles= 1
Profile Names=01pct
River Rch & RM=JAWBNRN,Main            ,6086
    86.9
River Rch & RM=JAWBNRN,Main            ,3250
     104
River Rch & RM=JAWBNRN,Main            ,2593
     116
River Rch & RM=JAWBNRN,Main            ,2058
     130
River Rch & RM=JAWBNRN,Main            ,1062
     158
Boundary for River Rch & Prof#=JAWBNRN,Main            , 1
Up Type= 0
Dn Type= 3
Dn Slope=0.01439
DSS Import GetInterval= 0
DSS Import GetPeak= 0
DSS Import FillOption= 0

--- JAWBNRN.g01 (geometry) ---

Geom Title=Geometry
Program Version=6.31

River Reach=JAWBNRN         ,Main
Reach XY= 30
2182577.58816776724140.0370173452182617.08480792724173.891280338
2182816.73729576724252.884232596 2182975.1575826724253.318286836
2183073.68199185 724196.460789012183148.76878393724202.103166178
2183246.85881084  724242.03353252183301.98041976724237.693318084
2183337.13684551724280.662064165 2183458.6644896724315.818161845
2183565.86932768724301.0613015892183597.11926517724267.207038596
   2183691.30346 724288.040658342183774.20257242724276.321849748
2183920.18444768724094.0789841662184048.07440001724049.759310752
2185312.77692309724486.9556148352185634.13126726724552.059487253
2185692.46448392724524.9762080912185789.14749172724357.006080382
2186141.91646436724460.2872014962186234.65204784724420.809749752
2186331.54417412724412.6287897032186362.01168034724379.153591287
2186459.65192592724365.0805305092187025.44765425724684.610028236
2187055.11628617725024.1228475872186940.53285393725307.976938665
2186920.13361651725581.4143839182186850.39983208725676.813799426

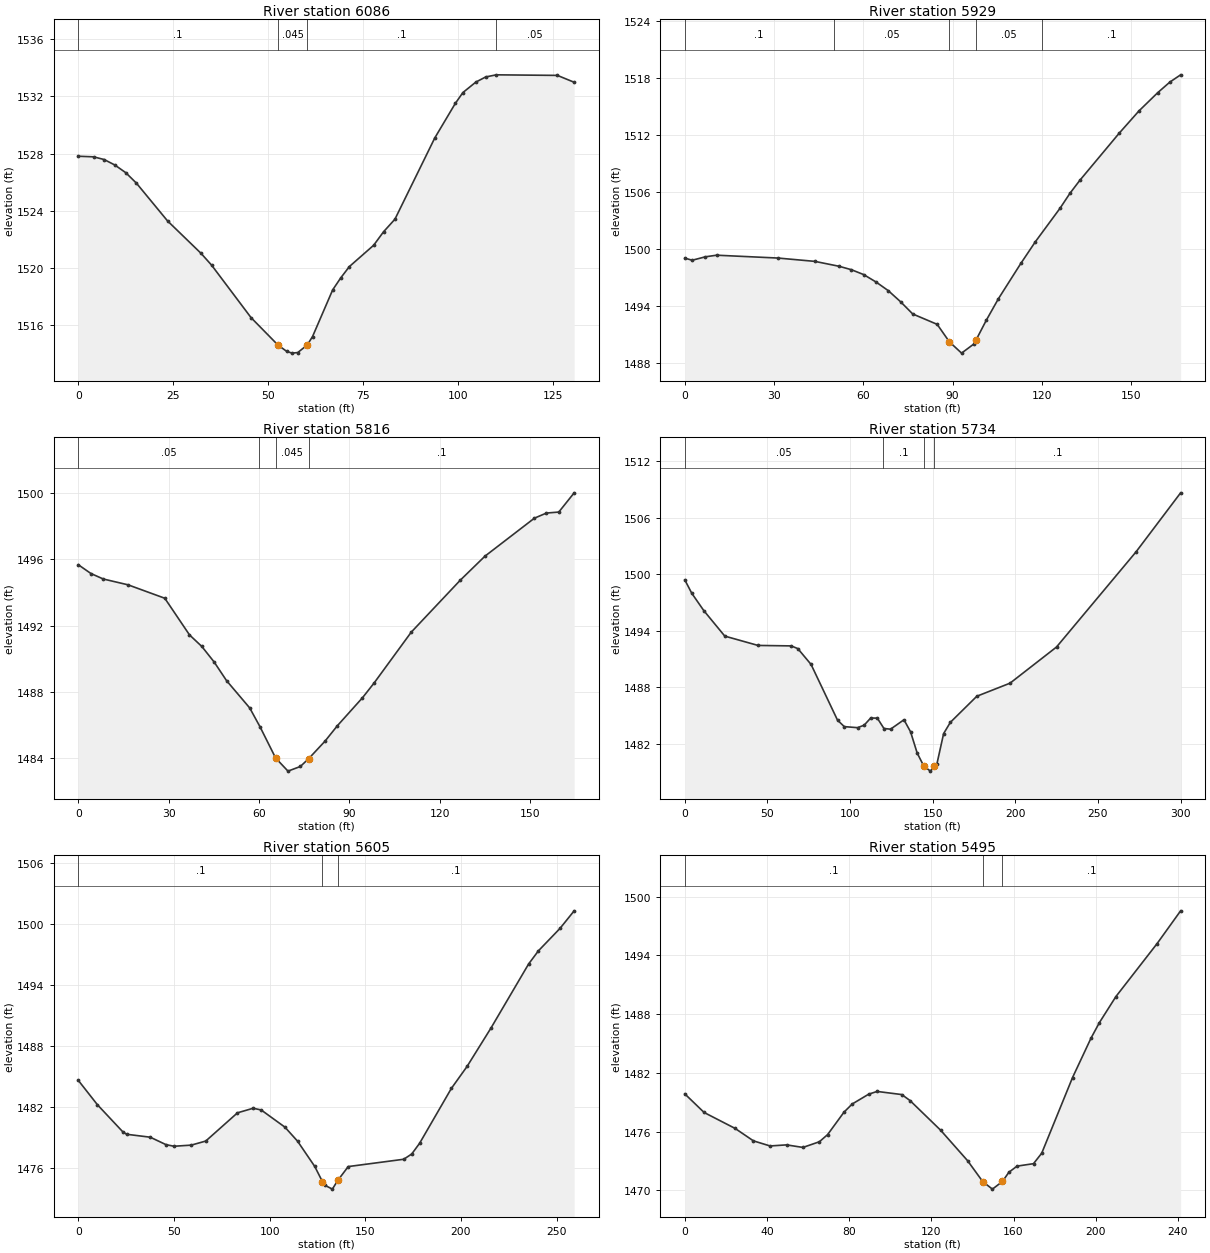
Type RM Length L Ch R = 1 ,6086    ,156.6,156.6,156.6
XS GIS Cut Line= 2
2182538.31745624724184.9199298342182635.44928734724097.599394804
#Sta/Elev= 30
       0 1527.81       4 1527.77     6.8 1527.58     9.6  1527.2    12.5 1526.66
    15.3 1525.93    23.5 1523.29    32.3 1521.03    35.1  1520.2    45.5 1516.53
    52.61514.612    54.9 1514.17    56.3 1514.05    57.8 1514.09    60.31514.617
    61.7 1515.21      67 1518.47    69.1  1519.3    71.4  1520.1    77.8 1521.59
    80.4 1522.53    83.4 1523.41    93.9 1529.09    99.3  1531.5   101.3 1532.26
   104.7 1532.99   107.3 1533.35   110.1  1533.5   126.2 1533.46130.6119 1532.98
#Mann= 4 ,-1,0
       0      .1       0    52.6    .045       0    60.3      .1       0
     110     .05       0
Bank Sta=52.6,60.3
XS Rating Curve= 0 ,0
Exp/Cntr(USF)=0,0
Exp/Cntr=0.3,0.1

Type RM Length L Ch R = 1 ,5929    ,113.1,113.1,113.1
XS GIS Cut Line= 2
2182702.28451923724287.614437638 2182741.6046681724125.767493501
#Sta/Elev= 30
       0 1499.03     2.5 1498.81     6.9 1499.17    10.7 1499.34    31.3 1499.04
    43.7 1498.69    51.9 1498.17      56 1497.81    60.1  1497.3    64.3 1496.51
    68.4  1495.6    72.5 1494.44    76.6 1493.15    84.8 1492.06    88.9 1490.22
      93 1489.03    97.2 1490.01    97.81490.373   101.3 1492.49   105.4 1494.77
   112.9 1498.47   117.8 1500.76   126.1 1504.29   129.4 1505.85   132.7 1507.21
     146  1512.2   152.6 1514.53   158.9 1516.45     163 1517.57   166.6 1518.33
#Mann= 5 ,-1,0
       0      .1       0      50     .05       0    88.9    .045       0
    97.8     .05       0     120      .1       0
Bank Sta=88.9,97.8
XS Rating Curve= 0 ,0
Exp/Cntr(USF)=0,0
Exp/Cntr=0.3,0.1

Type RM Length L Ch R = 1 ,5816    ,81.8,81.8,81.8
XS GIS Cut Line= 2
2182804.89703074724321.2975192412182838.78884321724160.181056889
#Sta/Elev= 26
       0 1495.67     4.2 1495.14     8.3 1494.81    16.5 1494.46    28.7 1493.65
    36.9 1491.44      41 1490.74    45.1  1489.8    49.2 1488.68    56.9 1487.03
    60.3  1485.9    65.5 1484.01    69.6 1483.22    73.7  1483.5   76.46 1483.97
    81.9 1485.03      86 1485.96    94.3 1487.64    98.2 1488.54   110.5  1491.6
   126.8 1494.74     135 1496.19   151.4 1498.48   155.4 1498.79   159.5 1498.85
   164.6 1500.01
#Mann= 4 ,-1,0
       0     .05       0      60      .1       0    65.5    .045       0
   76.46      .1       0
Bank Sta=65.5,76.46
XS Rating Curve= 0 ,0
Exp/Cntr(USF)=0,0
Exp/Cntr=0.3,0.1

Type RM Length L Ch R = 1 ,5734    ,129.8,129.8,129.8
XS GIS Cut Line= 2
2182886.57427623724389.3300200952182910.40702261724090.278184789
#Sta/Elev= 30
       0  1499.4     4.2 1497.98    11.5 1496.13    24.2 1493.42    44.3 1492.43
    64.4 1492.38    68.4 1492.09    76.4 1490.41    92.4 1484.49    96.5  1483.8
   104.5 1483.69   108.5 1483.95   112.5 1484.72   116.5  1484.7   120.5  1483.6
   124.5 1483.53   132.6 1484.53   136.6 1483.25   140.6 1480.99   144.6 1479.61
   148.6 1479.07     151 1479.57   152.6 1479.88   156.6 1483.06   160.7 1484.26
   176.7 1487.03   196.8 1488.42   224.9 1492.26     273 1502.37     300 1508.65
#Mann= 4 ,-1,0
       0     .05       0     120      .1       0   144.6    .045       0
     151      .1       0
Bank Sta=144.6,151
XS Rating Curve= 0 ,0
Exp/Cntr(USF)=0,0
Exp/Cntr=0.3,0.1

Type RM Length L Ch R = 1 ,5605    ,109.6,109.6,109.6
XS GIS Cut Line= 2
2183052.10395899724357.5185686482182985.15716893724107.111825051
#Sta/Elev= 30
       0  1484.6      10  1482.2    23.1 1479.57    25.2  1479.3    37.6 1479.01
    45.8 1478.28      50 1478.12      59 1478.23    66.6 1478.63    83.2 1481.41
    91.4 1481.86    95.6 1481.69     108    1480   114.6 1478.62   123.6 1476.13
   127.6 1474.64   128.7  1474.3   132.8  1473.9   135.61474.752   141.1 1476.12
   170.1 1476.84   174.3 1477.36   178.4 1478.41     195 1483.81   203.2 1485.97
   215.7 1489.75   235.4 1496.06   240.5 1497.35   251.8 1499.56   259.2 1501.29
#Mann= 3 ,-1,0
       0      .1       0   127.6    .045       0   135.6      .1       0
Bank Sta=127.6,135.6
XS Rating Curve= 0 ,0
Exp/Cntr(USF)=0,0
Exp/Cntr=0.3,0.1

Type RM Length L Ch R = 1 ,5495    ,125.4,125.4,125.4
XS GIS Cut Line= 2
2183105.75760355724350.5634144962183120.33818732724109.686701592
#Sta/Elev= 30
       0 1479.85     9.4 1477.95    24.5 1476.32    33.4 1475.05    41.5 1474.53
    49.5 1474.64    57.5 1474.38    65.5 1474.96    69.5 1475.69    77.5 1477.99
    81.5 1478.82    89.5 1479.82    93.6  1480.1   105.6 1479.78   109.6 1479.17
   124.5 1476.14   137.6 1473.03     145 1470.89   149.7 1470.12   154.61470.902
   157.7 1471.84   161.7 1472.47   169.7 1472.72   173.7 1473.79   188.7 1481.52
   197.7 1485.55   201.8 1487.14   209.8 1489.79   229.8 1495.19   241.3 1498.55
#Mann= 3 ,-1,0
       0      .1       0     145    .045       0   154.6      .1       0
Bank Sta=145,154.6
XS Rating Curve= 0 ,0
Exp/Cntr(USF)=0,0
Exp/Cntr=0.3,0.1

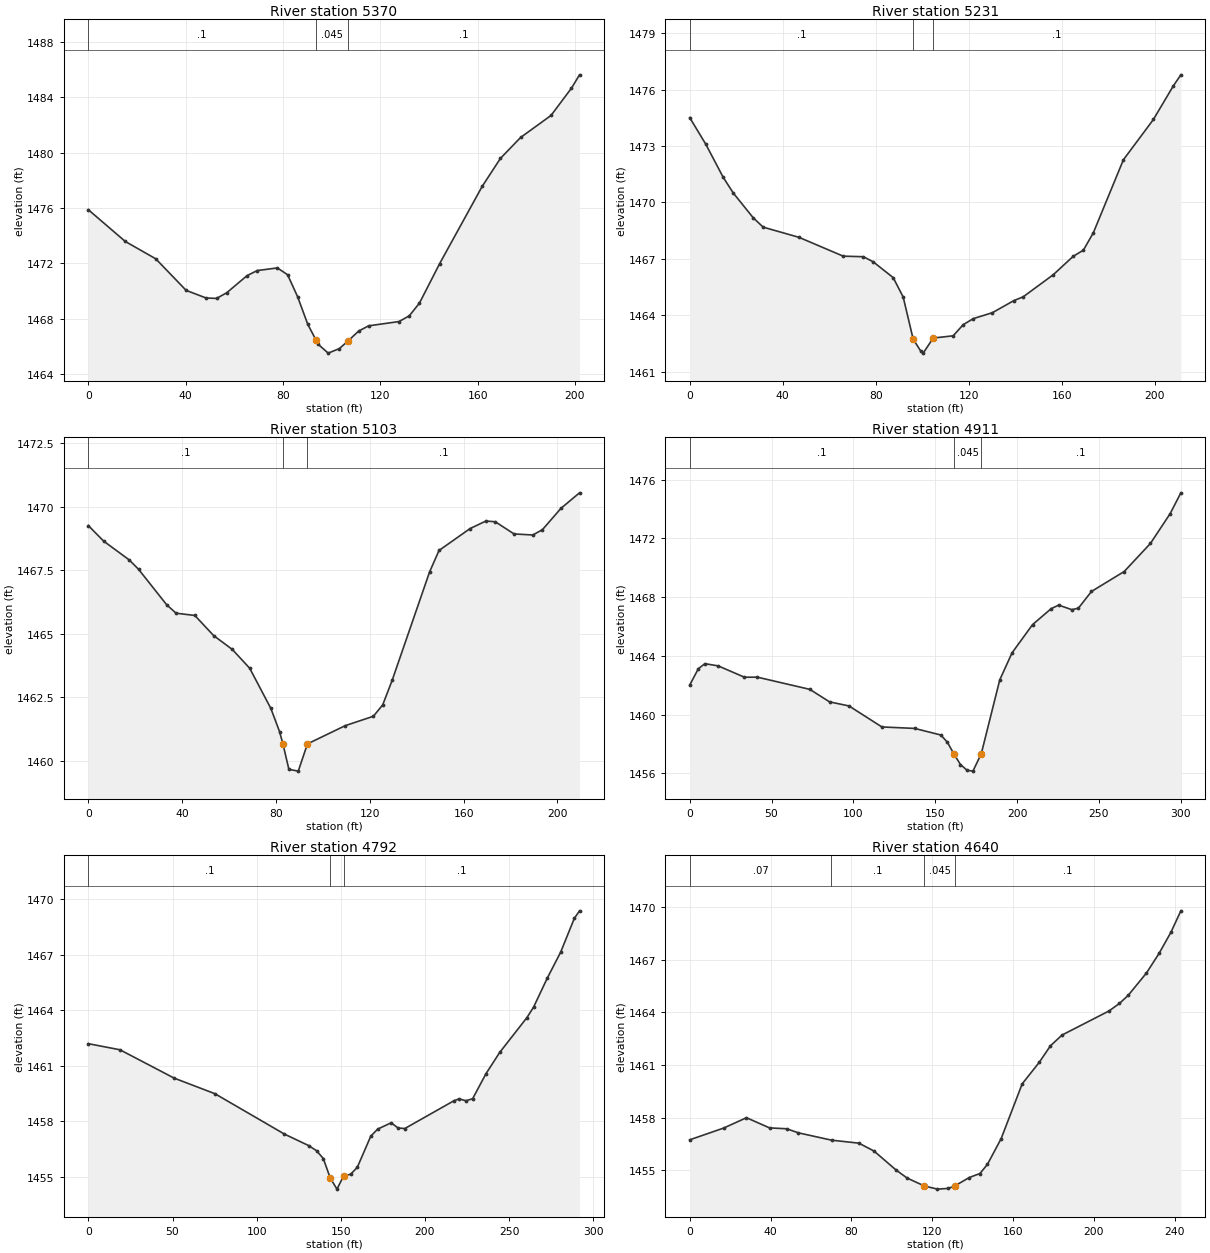
Type RM Length L Ch R = 1 ,5370    ,138.1,138.1,138.1
XS GIS Cut Line= 2
2183202.73423663 724331.769803242183259.38152053724138.010343541
#Sta/Elev= 30
       0 1475.87    15.2 1473.58    27.7 1472.33    40.2 1470.05    48.4  1469.5
    52.7 1469.47    56.9 1469.88    65.2 1471.11    69.4 1471.48    77.7 1471.67
    81.9 1471.18      86  1469.6    90.2  1467.6    93.5 1466.49    94.4 1466.17
    98.6 1465.52   103.2 1465.85   106.91466.422   111.1 1467.11   115.2 1467.49
   127.7  1467.8   131.9 1468.21   136.1 1469.13   144.4 1471.98   161.9 1477.56
   169.4 1479.58   177.7 1481.09   190.2 1482.68   198.6 1484.65   201.9 1485.61
#Mann= 3 ,-1,0
       0      .1       0    93.5    .045       0   106.9      .1       0
Bank Sta=93.5,106.9
XS Rating Curve= 0 ,0
Exp/Cntr(USF)=0,0
Exp/Cntr=0.3,0.1

Type RM Length L Ch R = 1 ,5231    ,128.5,128.5,128.5
XS GIS Cut Line= 2
2183304.51959823724374.524441555 2183382.3372434724178.159713333
#Sta/Elev= 30
       0 1474.51     6.9  1473.1    14.4 1471.34    18.7 1470.51    27.3 1469.19
    31.6 1468.69      47 1468.15      66 1467.15    74.7 1467.12    78.9 1466.85
    87.5 1466.01    91.8 1464.98    96.1 1462.74    99.4  1462.1   100.4    1462
   104.7  1462.8   113.3 1462.92   117.6 1463.51   121.9 1463.83   130.2 1464.15
   139.4 1464.79   143.4 1464.99   156.3 1466.16   164.9 1467.14   169.3 1467.47
   173.6  1468.4   186.5 1472.27   199.4 1474.41     208  1476.2   211.2 1476.78
#Mann= 3 ,-1,0
       0      .1       0    96.1    .045       0   104.7      .1       0
Bank Sta=96.1,104.7
XS Rating Curve= 0 ,0
Exp/Cntr(USF)=0,0
Exp/Cntr=0.3,0.1

Type RM Length L Ch R = 1 ,5103    ,192.1,192.1,192.1
XS GIS Cut Line= 2
2183457.00329504724402.5789081132183464.72792466 724193.37018917
#Sta/Elev= 30
       0 1469.26     6.5 1468.65    17.4 1467.91    21.4 1467.54    33.4 1466.14
    37.4 1465.81    45.4 1465.72    53.4 1464.93    61.4 1464.38    68.8 1463.64
    77.8 1462.06    81.5 1461.15   82.96 1460.66    85.5 1459.66    89.5 1459.59
    93.41460.662   109.5 1461.38   121.5 1461.75   125.5  1462.2   129.5 1463.16
   145.5 1467.44   149.5 1468.28   162.7 1469.14   169.5 1469.44   173.5 1469.41
   181.5 1468.93   189.5 1468.89   193.6  1469.1   201.5 1469.94   209.4 1470.55
#Mann= 3 ,-1,0
       0      .1       0   82.96    .045       0    93.4      .1       0
Bank Sta=82.96,93.4
XS Rating Curve= 0 ,0
Exp/Cntr(USF)=0,0
Exp/Cntr=0.3,0.1

Type RM Length L Ch R = 1 ,4911    ,118.7,118.7,118.7
XS GIS Cut Line= 2
2183623.73137389724438.5289221762183625.08474281 724138.53197487
#Sta/Elev= 30
       0 1462.01     5.3 1463.13     9.3 1463.47    17.4 1463.32    33.4 1462.55
    41.4 1462.55    73.4 1461.72    85.4 1460.87    97.3 1460.59   117.4 1459.16
   137.4 1459.06   153.4 1458.61   157.4 1458.12   161.4 1457.31   165.4  1456.6
   169.4 1456.21     173 1456.15   178.11457.336   189.4 1462.37   196.9 1464.21
   209.4 1466.13   220.8 1467.22   225.4 1467.46   233.4 1467.15   237.4 1467.25
   245.4 1468.39   265.4 1469.75   281.4 1471.66   293.4 1473.68     300 1475.11
#Mann= 3 ,-1,0
       0      .1       0   161.4    .045       0   178.1      .1       0
Bank Sta=161.4,178.1
XS Rating Curve= 0 ,0
Exp/Cntr(USF)=0,0
Exp/Cntr=0.3,0.1

Type RM Length L Ch R = 1 ,4792    ,151.9,151.9,151.9
XS GIS Cut Line= 2
2183755.04525464724423.8216395752183720.28442134 724134.14802873
#Sta/Elev= 30
       0  1462.2    18.8 1461.87      51 1460.34    75.2  1459.5   116.5 1457.32
   130.9  1456.7   135.6 1456.42   139.6    1456   143.7 1454.95   147.7 1454.35
   151.7 1455.07   155.8 1455.15   159.8 1455.53   167.8 1457.21   171.9 1457.59
   179.9 1457.93     184 1457.65     188 1457.62   217.2 1459.12   220.2 1459.22
   224.4 1459.12   228.3 1459.23   236.3 1460.59   244.4 1461.73   260.5  1463.6
   264.5 1464.17   272.6 1465.73   280.6 1467.14   288.7 1468.96   291.8 1469.37
#Mann= 3 ,-1,0
       0      .1       0   143.7    .045       0   151.7      .1       0
Bank Sta=143.7,151.7
XS Rating Curve= 0 ,0
Exp/Cntr(USF)=0,0
Exp/Cntr=0.3,0.1

Type RM Length L Ch R = 1 ,4640    ,140.7,140.7,140.7
XS GIS Cut Line= 2
2183941.72380385 724271.260204532183756.33269291724114.192735539
#Sta/Elev= 30
       0 1456.73    16.8  1457.4    28.1 1457.99    39.5 1457.41      48 1457.36
    53.7 1457.13    70.2 1456.71    83.7 1456.54    91.2 1456.09   102.2    1455
   107.6 1454.55   116.1  1454.1   122.6 1453.92   127.9 1453.96   131.11454.099
   138.3 1454.58   143.6 1454.81   147.3 1455.33   154.1  1456.8   164.5 1459.92
   172.9 1461.14   178.5 1462.09   184.2  1462.7   207.4 1464.07   212.6  1464.5
     217 1464.97     226 1466.24   232.2 1467.35   238.1 1468.56     243 1469.78
#Mann= 4 ,-1,0
       0     .07       0      70      .1       0   116.1    .045       0
   131.1      .1       0
Bank Sta=116.1,131.1
XS Rating Curve= 0 ,0
Exp/Cntr(USF)=0,0
Exp/Cntr=0.3,0.1

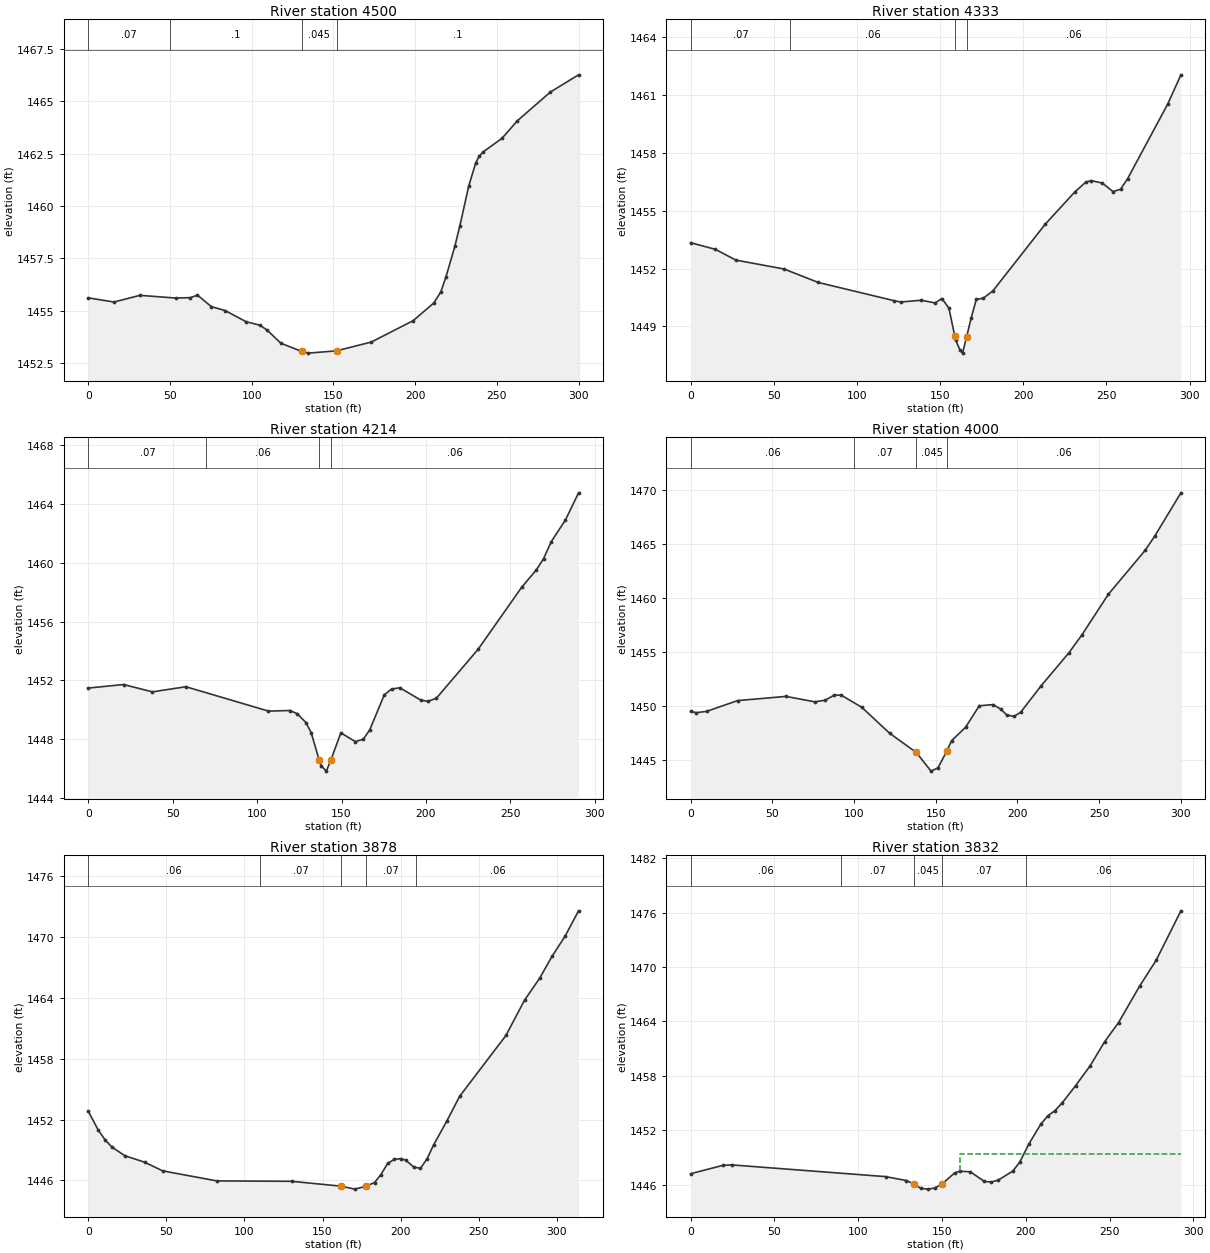
Type RM Length L Ch R = 1 ,4500    ,166,166,166
XS GIS Cut Line= 2
2183981.94461924724215.9477188062183879.32899336723934.043420641
#Sta/Elev= 30
       0 1455.61    15.7 1455.41    31.6 1455.73    53.5  1455.6    62.5 1455.62
    66.8 1455.74    75.3 1455.19    83.8    1455    96.6 1454.47   105.1  1454.3
   109.4 1454.07   117.9 1453.44   130.6 1453.05   134.6 1452.97   151.9 1453.08
   173.2  1453.5   198.8 1454.52   211.5 1455.37   215.8 1455.91   218.9 1456.62
   224.3 1458.07   227.4 1459.06   232.8 1460.95   237.1 1462.06   239.1 1462.36
   241.3 1462.56   253.2 1463.23   262.6 1464.07   282.8 1465.44     300 1466.26
#Mann= 4 ,-1,0
       0     .07       0      50      .1       0   130.6    .045       0
   151.9      .1       0
Bank Sta=130.6,151.9
XS Rating Curve= 0 ,0
Exp/Cntr(USF)=0,0
Exp/Cntr=0.3,0.1

Type RM Length L Ch R = 1 ,4333    ,119.3,119.3,119.3
XS GIS Cut Line= 2
2184049.10029597724223.519418979 2184122.6850165723938.010703316
#Sta/Elev= 30
       0 1453.34    14.8    1453    27.2 1452.44    56.1 1451.98    76.8 1451.28
   122.2 1450.34   126.3 1450.27   138.7 1450.36     147 1450.22   151.1 1450.45
   155.3 1449.95   158.8 1448.51   159.4 1448.28   162.1 1447.76   163.5 1447.62
   165.9 1448.45   168.7 1449.45   171.8 1450.41   175.9 1450.46   181.8 1450.85
   213.1 1454.29   231.1 1455.98   237.6 1456.48   240.9 1456.56   247.5 1456.43
     254 1455.99   258.5 1456.11   262.7 1456.65   286.9 1460.53   294.8 1462.04
#Mann= 4 ,-1,0
       0     .07       0      60     .06       0   158.8    .045       0
   165.9     .06       0
Bank Sta=158.8,165.9
XS Rating Curve= 0 ,0
Exp/Cntr(USF)=0,0
Exp/Cntr=0.3,0.1

Type RM Length L Ch R = 1 ,4214    ,213.9,213.9,213.9
XS GIS Cut Line= 2
2184148.90924525724236.6446571952184253.85844091723965.840032531
#Sta/Elev= 30
       0 1451.47    20.9 1451.71      38 1451.21    57.8 1451.56   106.7  1449.9
   119.5 1449.94   123.8 1449.72   128.9 1449.12     132 1448.44   136.7 1446.59
   138.1 1446.16     141 1445.81   143.71446.568   149.6 1448.42   158.2 1447.82
   162.9 1447.98   166.7 1448.62   175.3    1451   179.6  1451.4   184.5 1451.49
   196.8 1450.66   201.1 1450.56   206.2 1450.78   230.9 1454.11   256.8 1458.35
   265.4 1459.52   269.7 1460.29   274.2 1461.44   282.6 1462.91   290.4 1464.77
#Mann= 4 ,-1,0
       0     .07       0      70     .06       0   136.7    .045       0
   143.7     .06       0
Bank Sta=136.7,143.7
XS Rating Curve= 0 ,0
Exp/Cntr(USF)=0,0
Exp/Cntr=0.3,0.1

Type RM Length L Ch R = 1 ,4000    ,122.2,122.2,122.2
XS GIS Cut Line= 2
2184354.99884299724312.3757328492184451.76910587724028.411798129
#Sta/Elev= 30
       0 1449.48     3.4 1449.35     9.7 1449.47    28.7 1450.47    58.3 1450.86
    75.9 1450.36    82.2  1450.5    87.9 1450.98    92.1 1450.98   104.8 1449.84
   121.7 1447.45   138.11445.658   147.1 1443.93   151.3 1444.23   156.7 1445.77
   159.7 1446.76   168.2 1447.99   176.6 1449.99   185.1  1450.1   189.7 1449.68
   193.5 1449.14   197.8    1449     202  1449.4   214.6 1451.87   231.6 1454.93
   239.3 1456.54   255.6 1460.33   278.1  1464.4     284 1465.73     300 1469.74
#Mann= 4 ,-1,0
       0     .06       0     100     .07       0   138.1    .045       0
   156.7     .06       0
Bank Sta=138.1,156.7
XS Rating Curve= 0 ,0
Exp/Cntr(USF)=0,0
Exp/Cntr=0.3,0.1

Type RM Length L Ch R = 1 ,3878    ,46.3,46.3,46.3
XS GIS Cut Line= 2
2184466.41543154724371.4714510732184563.51312253724072.980582619
#Sta/Elev= 30
       0 1452.81     6.4 1450.95    10.8 1449.99      15  1449.3    23.4 1448.43
    36.1 1447.79    47.6 1446.94    82.3 1445.95   130.2 1445.91   161.81445.433
   170.7 1445.14   177.71445.424   183.3 1445.79   187.3 1446.57   191.7 1447.67
   195.9 1448.07   200.1 1448.15   203.2 1447.99   208.5 1447.31   212.7 1447.19
   216.9 1448.13   221.1  1449.5   229.6 1451.86   237.7 1454.27   267.4 1460.28
   279.3 1463.75   288.9  1465.9   296.9 1468.07   305.3 1470.07   313.9 1472.56
#Mann= 5 ,-1,0
       0     .06       0     110     .07       0   161.8    .045       0
   177.7     .07       0     210     .06       0
Bank Sta=161.8,177.7
XS Rating Curve= 0 ,0
Exp/Cntr(USF)=0,0
Exp/Cntr=0.3,0.1

Type RM Length L Ch R = 1 ,3832    ,53.9,53.9,53.9
XS GIS Cut Line= 2
2184519.36229022 724355.545909462184611.58847328724077.886230654
#Sta/Elev= 30
       0  1447.2    19.4 1448.13    24.7 1448.17   116.3 1446.88   128.7 1446.45
   133.2 1446.07   137.4 1445.59   141.6  1445.5   145.8 1445.63     150 1446.06
   157.5 1447.28   160.7 1447.48   166.9 1447.41   175.3 1446.35   179.5 1446.28
   183.7 1446.51   192.2 1447.48   196.4 1448.47   201.8 1450.46     209 1452.67
   213.2 1453.59   217.5 1454.17   221.7    1455   229.7  1456.9   238.5 1459.12
     247 1461.74   255.4 1463.87     268  1467.9   277.8 1470.73   292.6 1476.19
#Mann= 5 ,-1,0
       0     .06       0      90     .07       0   133.2    .045       0
     150     .07       0     200     .06       0
#XS Ineff= 2 , 0
                          160.56         1449.42
Permanent Ineff=
       F       F
Bank Sta=133.2,150
XS Rating Curve= 0 ,0
Exp/Cntr(USF)=0,0
Exp/Cntr=0.3,0.1

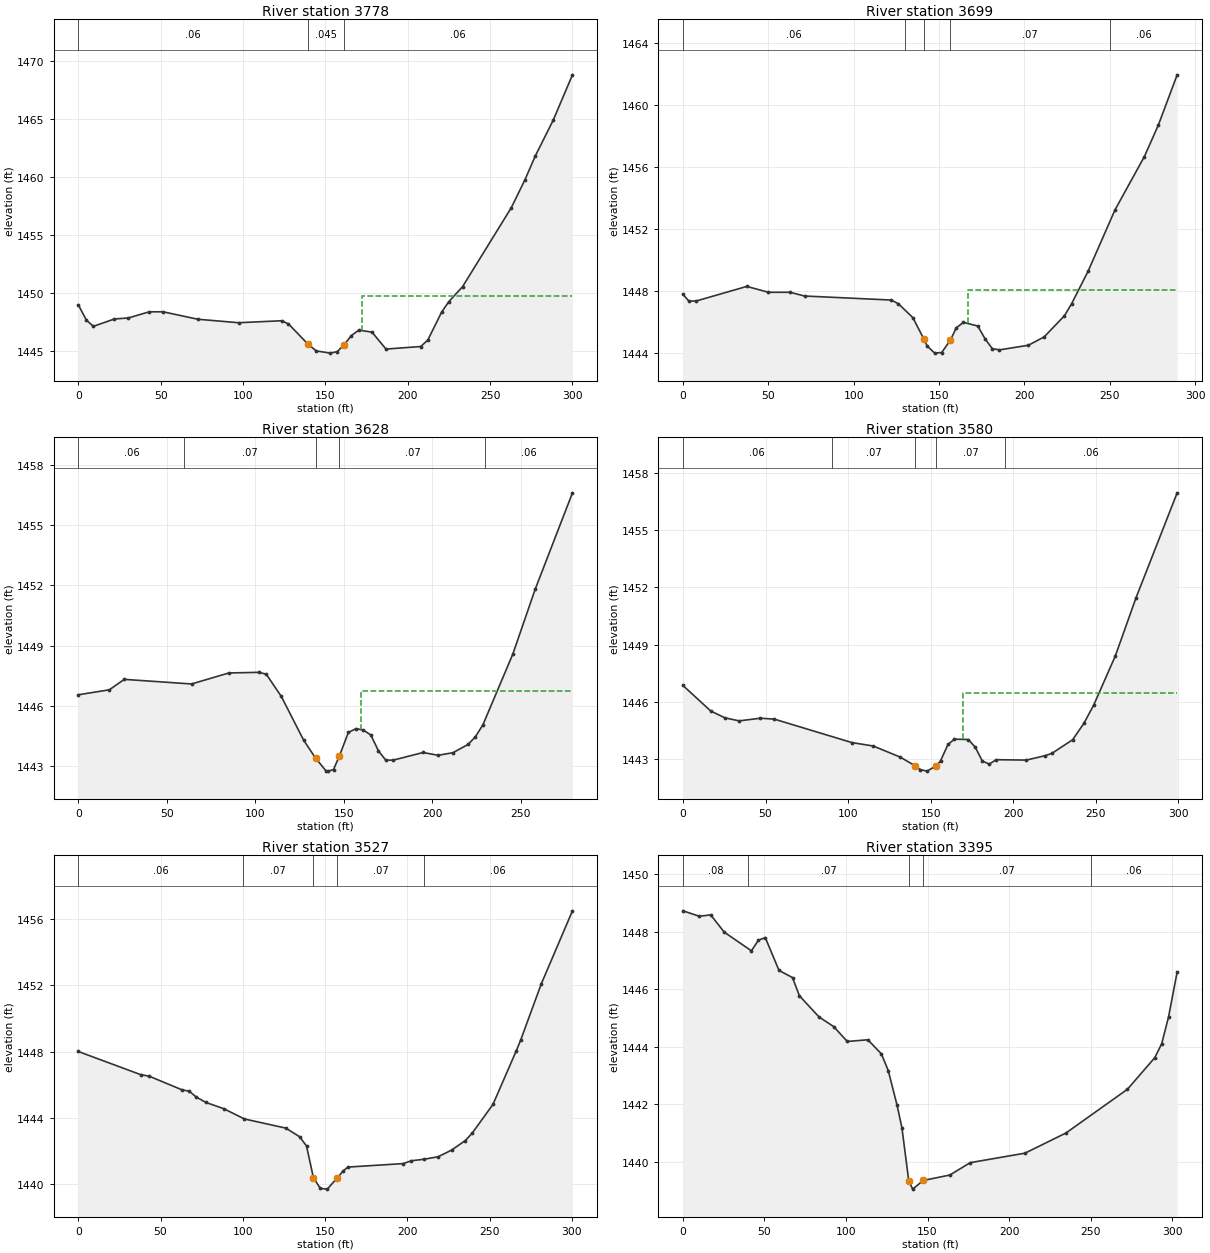
Type RM Length L Ch R = 1 ,3778    ,78.9,78.9,78.9
XS GIS Cut Line= 2
2184564.66591167724385.9112542812184661.78152655724102.065244361
#Sta/Elev= 30
       0 1448.97       5 1447.63     9.2 1447.11    21.9 1447.74    30.4 1447.83
    43.1 1448.36    51.5 1448.36    72.6 1447.72    97.3 1447.42   123.4 1447.59
   127.6 1447.32   139.61445.553   144.5 1444.99     153  1444.8   157.2 1444.93
   161.4 1445.52   165.7  1446.3   170.3 1446.78   178.3 1446.61   186.8 1445.15
   207.9 1445.37   212.2 1445.93   220.6 1448.34   224.8 1449.21   233.3 1450.53
   262.9 1457.34   271.1 1459.72   277.4 1461.78   288.3 1464.87     300 1468.78
#Mann= 3 ,-1,0
       0     .06       0   139.6    .045       0   161.4     .06       0
#XS Ineff= 2 , 0
                          172.23         1449.72
Permanent Ineff=
       F       F
Bank Sta=139.6,161.4
XS Rating Curve= 0 ,0
Exp/Cntr(USF)=0,0
Exp/Cntr=0.3,0.1

Type RM Length L Ch R = 1 ,3699    ,70.8,70.8,70.8
XS GIS Cut Line= 2
2184640.04123189724408.5269082432184734.22967417724134.791747866
#Sta/Elev= 30
       0 1447.77     3.5 1447.33     7.8 1447.34    37.4 1448.28    50.1  1447.9
    62.8  1447.9    71.2 1447.66     122  1447.4   126.2 1447.16   134.7 1446.26
   141.2 1444.86   143.1 1444.42   147.5 1443.97   151.6 1444.01   156.71444.817
   160.1  1445.6   164.3 1445.96   172.7 1445.72     177 1444.89   181.2 1444.26
   185.4 1444.18   202.4 1444.48   211.6 1445.02   223.5 1446.39   227.7 1447.17
   237.4 1449.28   253.1 1453.23   270.3 1456.67   278.5 1458.71   289.5 1461.95
#Mann= 5 ,-1,0
       0     .06       0     130     .07       0   141.2    .045       0
   156.7     .07       0     250     .06       0
#XS Ineff= 2 , 0
                          166.82         1448.05
Permanent Ineff=
       F       F
Bank Sta=141.2,156.7
XS Rating Curve= 0 ,0
Exp/Cntr(USF)=0,0
Exp/Cntr=0.3,0.1

Type RM Length L Ch R = 1 ,3628    ,48.3,48.3,48.3
XS GIS Cut Line= 2
2184709.99866699724425.8570896332184799.00674494724161.217000713
#Sta/Elev= 30
       0 1446.54    17.6 1446.79      26 1447.31      64 1447.08    85.1 1447.63
     102 1447.66   106.2 1447.57   114.7 1446.46   127.3 1444.28   134.11443.374
     140 1442.74   141.2 1442.73   144.2 1442.81   147.5 1443.48   152.6 1444.66
   156.9 1444.85   161.1 1444.78   165.3 1444.53   169.6 1443.74   173.7 1443.28
     178 1443.28   194.8 1443.66   203.3 1443.52   211.7 1443.65   220.2 1444.06
   224.4 1444.45   228.6 1445.04   245.5 1448.57   258.1  1451.8   279.2 1456.62
#Mann= 5 ,-1,0
       0     .06       0      60     .07       0   134.1    .045       0
   147.5     .07       0     230     .06       0
#XS Ineff= 2 , 0
                          159.72         1446.75
Permanent Ineff=
       F       F
Bank Sta=134.1,147.5
XS Rating Curve= 0 ,0
Exp/Cntr(USF)=0,0
Exp/Cntr=0.3,0.1

Type RM Length L Ch R = 1 ,3580    ,53.4,53.4,53.4
XS GIS Cut Line= 4
2184763.24457077724452.8773990122184802.98031985724349.564451386
2184794.23845505 724305.855127392184839.53720901724169.164150531
#Sta/Elev= 30
       0 1446.85    16.8 1445.51    25.4 1445.15      34 1444.99    46.9 1445.13
    55.4 1445.08   102.3 1443.85   115.2 1443.67   131.5 1443.09   140.6 1442.63
   143.7 1442.43   147.8 1442.35   153.5 1442.63     156 1442.89   160.5 1443.75
   164.4 1444.03   172.8 1444.01     177 1443.61   181.3 1442.88   185.5 1442.72
   189.7 1442.95     208 1442.93   219.2 1443.16   223.4 1443.28     236    1444
   242.8 1444.86   248.7 1445.81   261.8 1448.39   274.4 1451.46   299.3 1456.97
#Mann= 5 ,-1,0
       0     .06       0      90     .07       0   140.6    .045       0
   153.5     .07       0  195.27     .06       0
#XS Ineff= 2 , 0
                          169.35         1446.46
Permanent Ineff=
       F       F
Bank Sta=140.6,153.5
XS Rating Curve= 0 ,0
Exp/Cntr(USF)=0,0
Exp/Cntr=0.3,0.1

Type RM Length L Ch R = 1 ,3527    ,131.5,131.5,131.5
XS GIS Cut Line= 2
2184802.43184424724465.4596094482184892.93222118724179.141477303
#Sta/Elev= 30
       0 1448.01      38 1446.61    43.1 1446.52    63.2 1445.69    67.4 1445.62
    71.6 1445.27    77.5 1444.94    88.4 1444.56     101 1443.94   126.1 1443.39
   134.5 1442.87   138.7 1442.31   142.9  1440.4   147.1 1439.75   151.3 1439.71
   157.31440.376     161 1440.81   163.9 1441.04   197.5 1441.25   202.4 1441.42
     210 1441.51   218.6 1441.66   226.8 1442.06   235.2 1442.64   239.4 1443.09
     252 1444.82   266.2 1448.06   268.8 1448.69   281.4  1452.1   300.3 1456.49
#Mann= 5 ,-1,0
       0     .06       0     100     .07       0   142.9    .045       0
   157.3     .07       0     210     .06       0
Bank Sta=142.9,157.3
XS Rating Curve= 0 ,0
Exp/Cntr(USF)=0,0
Exp/Cntr=0.3,0.1

Type RM Length L Ch R = 1 ,3395    ,144.7,144.7,144.7
XS GIS Cut Line= 2
2184927.75057199724501.355012899 2185018.3480799724212.078759545
#Sta/Elev= 30
       0 1448.72    10.1 1448.53      17 1448.58    25.3 1447.98      42 1447.33
    46.3  1447.7    50.5 1447.79    58.9 1446.65    67.2  1446.4    71.4 1445.77
    83.5 1445.03    92.4  1444.7   100.8 1444.18   113.4 1444.24   121.7 1443.75
   125.9 1443.17   131.3 1441.97   134.3 1441.18   138.5 1439.33   140.9 1439.05
   147.3 1439.35   163.7 1439.54   176.2 1439.97   209.8  1440.3   234.9    1441
   272.6 1442.52   289.4 1443.62   293.6  1444.1   297.8 1445.03   303.1  1446.6
#Mann= 5 ,-1,0
       0     .08       0      40     .07       0   138.5    .045       0
   147.3     .07       0     250     .06       0
Bank Sta=138.5,147.3
XS Rating Curve= 0 ,0
Exp/Cntr(USF)=0,0
Exp/Cntr=0.3,0.1

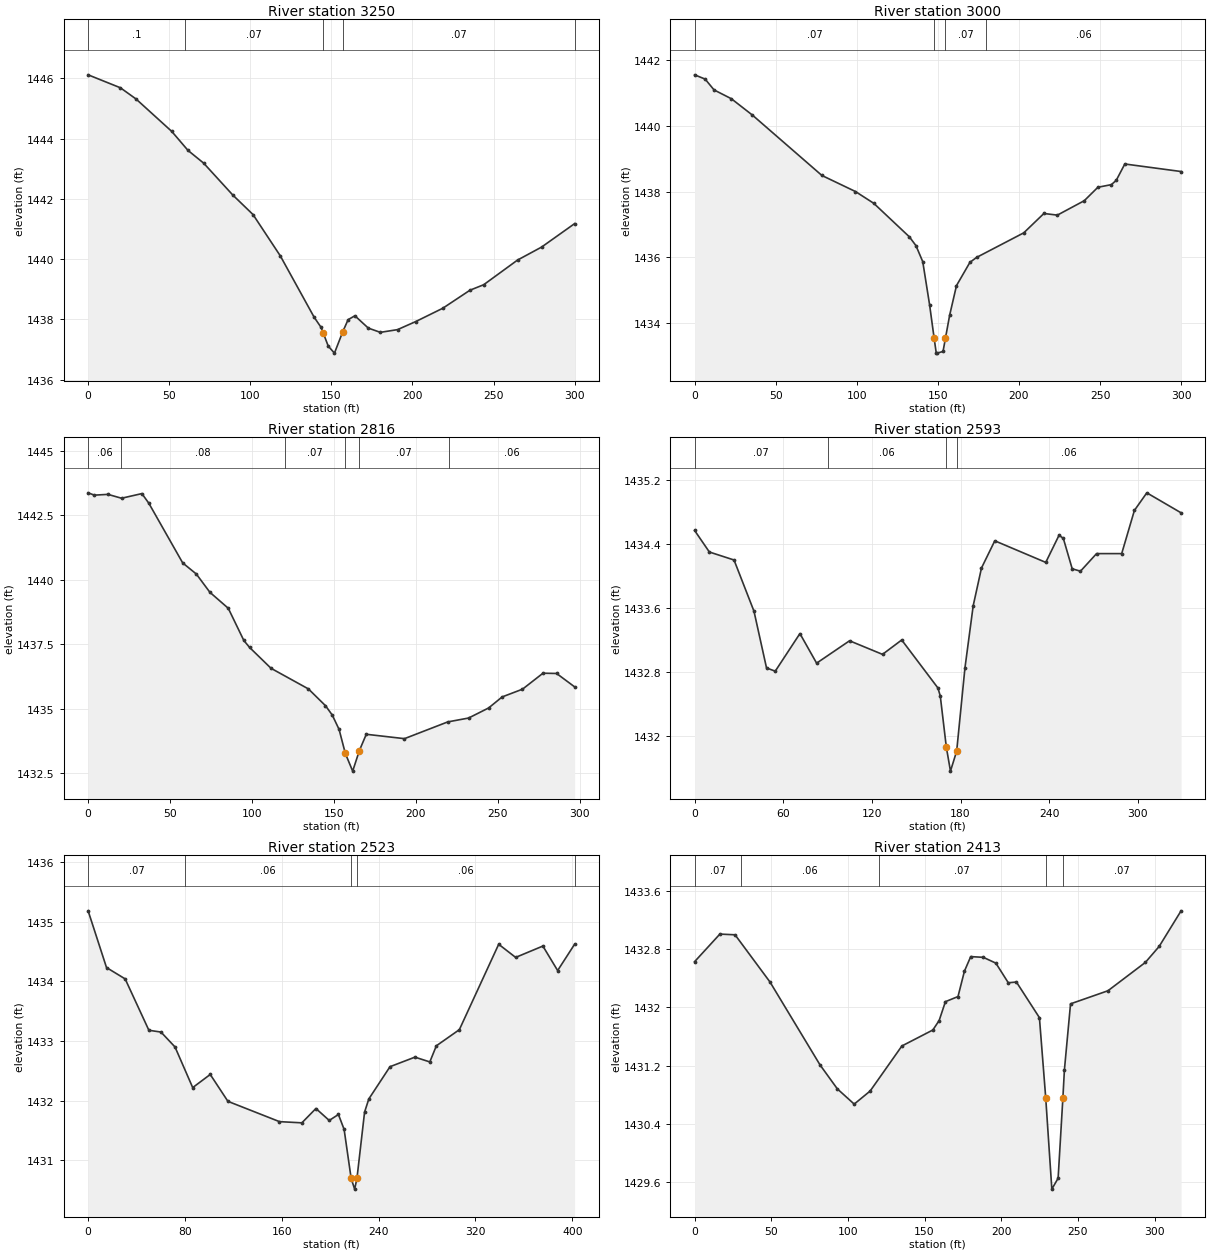
Type RM Length L Ch R = 1 ,3250    ,250,250,250
XS GIS Cut Line= 2
2185060.75326696724554.5393904322185147.91373791724267.480071993
#Sta/Elev= 27
       0 1446.12    19.9 1445.69    29.5 1445.32    51.6 1444.24    61.6 1443.61
    71.2 1443.19    89.2 1442.13   101.7 1441.48   118.5 1440.11   139.4 1438.07
   143.6 1437.74   144.9 1437.56   148.1 1437.11   151.9 1436.88   156.91437.573
   160.3 1437.99   164.5 1438.12   172.8 1437.71   180.2 1437.57   190.8 1437.66
   202.1 1437.93   218.7 1438.37   235.5 1438.97   243.9 1439.15   264.8 1439.97
   279.6  1440.4     300 1441.18
#Mann= 5 ,-1,0
       0      .1       0      60     .07       0   144.9    .045       0
   156.9     .07       0     300     .06       0
Bank Sta=144.9,156.9
XS Rating Curve= 0 ,0
Exp/Cntr(USF)=0,0
Exp/Cntr=0.3,0.1

Type RM Length L Ch R = 1 ,3000    ,184.8,184.8,184.8
XS GIS Cut Line= 2
2185287.80136358724632.7863916862185367.97034505724343.696553729
#Sta/Elev= 30
       0 1441.56     6.5 1441.43      12  1441.1    22.7 1440.83    35.7 1440.33
    78.5 1438.49    99.2    1438   110.5 1437.64   132.4 1436.62   136.5 1436.35
   140.7 1435.86   144.9 1434.55   147.71433.532     149 1433.08   149.5 1433.07
   153.2 1433.12   154.71433.526   157.3 1434.23   161.5 1435.13   169.8 1435.84
   173.9 1435.99     203 1436.74   215.4 1437.33   223.7 1437.28   240.3 1437.72
   248.7 1438.13     257 1438.21     260 1438.34   265.3 1438.84     300 1438.61
#Mann= 4 ,-1,0
       0     .07       0   147.7    .045       0   154.7     .07       0
     180     .06       0
Bank Sta=147.7,154.7
XS Rating Curve= 0 ,0
Exp/Cntr(USF)=0,0
Exp/Cntr=0.3,0.1

Type RM Length L Ch R = 1 ,2816    ,222.4,222.4,222.4
XS GIS Cut Line= 2
2185466.79184454724676.837787644 2185545.0734284724390.559751913
#Sta/Elev= 30
       0 1443.37     3.8 1443.28    12.1 1443.31    20.4 1443.16    32.8 1443.34
      37 1442.97    57.7 1440.65      66 1440.22    74.3 1439.51    85.5 1438.89
      95 1437.64    98.5 1437.37   111.6 1436.56   134.4 1435.76   144.8 1435.11
   148.9 1434.75   153.1 1434.19   156.9 1433.26   161.4 1432.57   165.5 1433.37
   169.7    1434     193 1433.83   219.4 1434.48   232.1 1434.63   244.3 1435.02
   252.6 1435.45     265 1435.75   277.5 1436.37   285.8 1436.36   296.8 1435.84
#Mann= 6 ,-1,0
       0     .06       0      20     .08       0     120     .07       0
   156.9    .045       0   165.5     .07       0     220     .06       0
Bank Sta=156.9,165.5
XS Rating Curve= 0 ,0
Exp/Cntr(USF)=0,0
Exp/Cntr=0.3,0.1

Type RM Length L Ch R = 1 ,2593    ,70,70,70
XS GIS Cut Line= 2
2185831.34150623724626.9199800142185595.31115665 724397.24735029
#Sta/Elev= 30
       0 1434.57      10  1434.3    26.7  1434.2    40.2 1433.56    48.7 1432.85
    54.6 1432.81    71.3 1433.28    82.6 1432.91   104.9 1433.19   127.2 1433.02
   140.2  1433.2   164.7  1432.6   166.3  1432.5   170.4 1431.86   173.2 1431.56
   177.4 1431.81     183 1432.85   188.6 1433.63   194.2  1434.1   203.2 1434.44
   237.7 1434.17   246.7 1434.51   249.6 1434.47   255.6 1434.09   261.2 1434.06
   272.1 1434.28   289.1 1434.28   297.7 1434.82   306.1 1435.04   329.3 1434.79
#Mann= 4 ,-1,0
       0     .07       0      90     .06       0   170.4    .045       0
   177.4     .06       0
Bank Sta=170.4,177.4
XS Rating Curve= 0 ,0
Exp/Cntr(USF)=0,0
Exp/Cntr=0.3,0.1

Type RM Length L Ch R = 1 ,2523    ,109.8,109.8,109.8
XS GIS Cut Line= 4
2185856.12561148 724632.009090722185735.03305261724434.110083707
2185724.70175785724391.9901896752185746.84020064 724267.38798745
#Sta/Elev= 30
       0 1435.18    15.2 1434.23    30.6 1434.04    50.2 1433.18    60.2 1433.15
    71.8  1432.9    86.4 1432.22   100.9 1432.44   115.5 1431.99   158.1 1431.65
   176.6 1431.63   188.2 1431.87   199.2 1431.67   206.8 1431.77   211.5 1431.52
   217.3  1430.7   220.2 1430.52   222.1  1430.7   228.4 1431.81   231.9 1432.03
   249.4 1432.57     270 1432.73   282.3 1432.65   287.7 1432.92   306.7 1433.19
   339.2 1434.62   353.2  1434.4   375.7 1434.59   387.9 1434.18   401.9 1434.62
#Mann= 5 ,-1,0
       0     .07       0      80     .06       0   217.3    .045       0
   222.1     .06       0  401.93     .07       0
Bank Sta=217.3,222.1
XS Rating Curve= 0 ,0
Exp/Cntr(USF)=0,0
Exp/Cntr=0.3,0.1

Type RM Length L Ch R = 1 ,2413    ,178.6,178.6,178.6
XS GIS Cut Line= 4
2185877.73085681724567.331332942 2185801.9370519724440.956674286
2185791.60575714724398.8367802542185813.74419993724274.234578029
#Sta/Elev= 30
       0 1432.63    16.5 1433.01    26.4    1433    49.2 1432.35    81.8 1431.21
    93.1 1430.88   104.1 1430.67   114.5 1430.85   135.2 1431.47   155.4 1431.69
   159.5 1431.82   163.6 1432.08   171.8 1432.15     176  1432.5   180.1  1432.7
   188.3 1432.69   196.5 1432.61   204.6 1432.34   209.9 1432.35   224.9 1431.86
     229 1430.76     233  1429.5   237.1 1429.65   240.21430.752   241.2 1431.14
   245.2 1432.05   269.6 1432.23     294 1432.62     303 1432.84   317.3 1433.33
#Mann= 5 ,-1,0
       0     .07       0      30     .06       0     120     .07       0
     229    .045       0   240.2     .07       0
Bank Sta=229,240.2
XS Rating Curve= 0 ,0
Exp/Cntr(USF)=0,0
Exp/Cntr=0.3,0.1