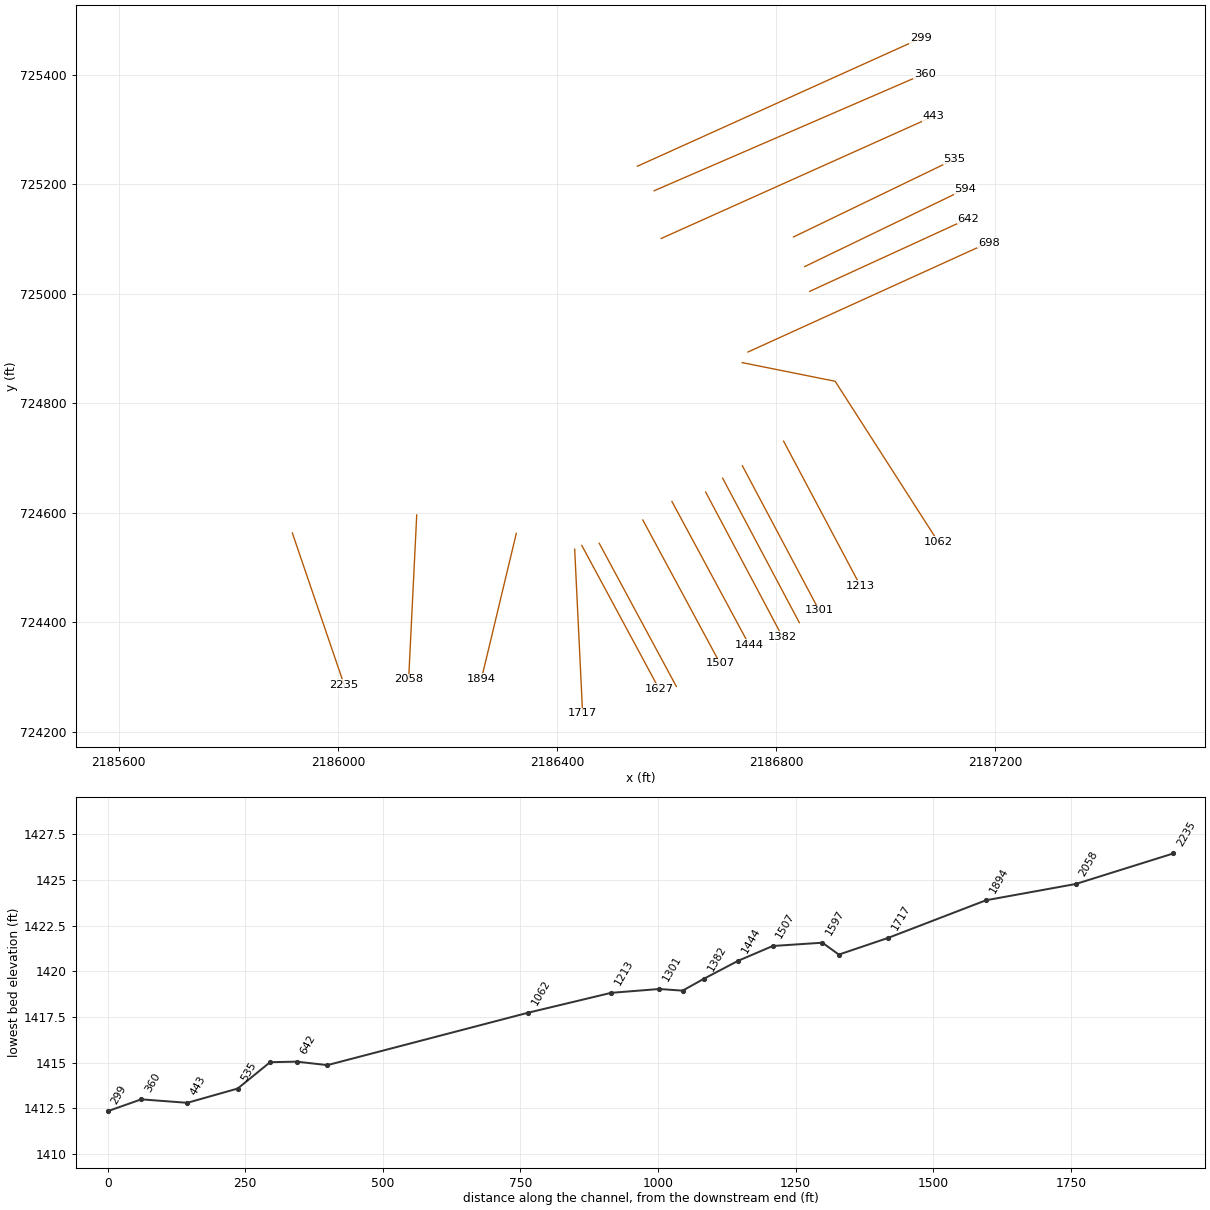
HEC-RAS study JAWBNRN.prj: JAWBNRN

--- JAWBNRN.g01 (geometry) --- (continued)

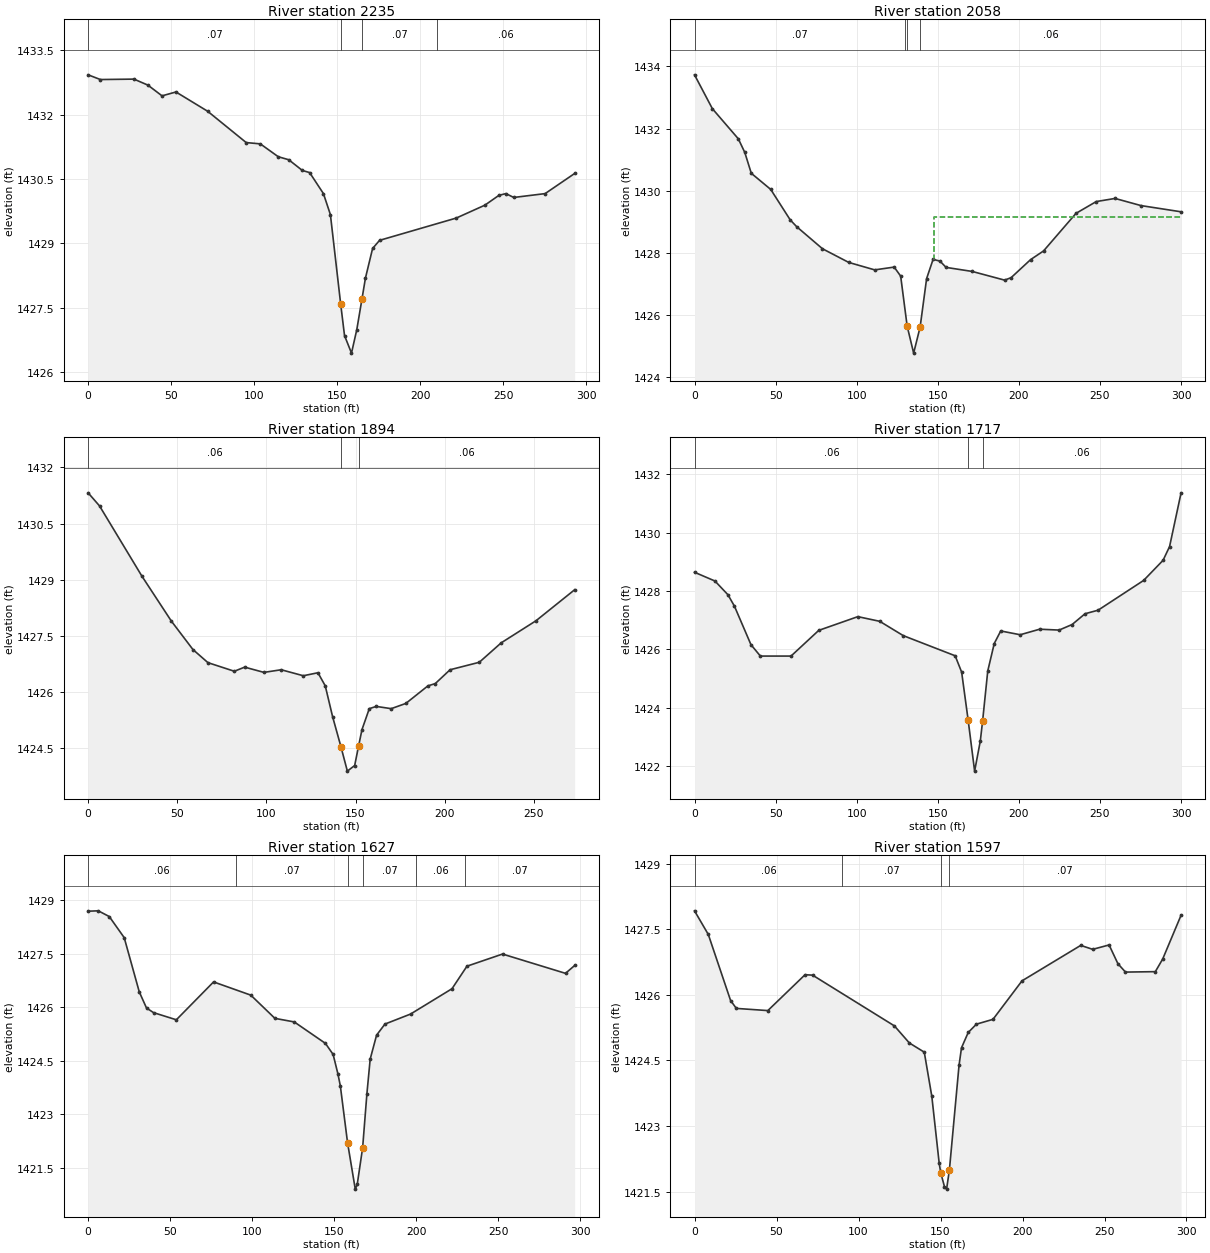
Type RM Length L Ch R = 1 ,2235    ,177.3,177.3,177.3
XS GIS Cut Line= 2
2185916.90853965724563.2768880892186011.51488469724286.023153605
#Sta/Elev= 30
       0 1432.93     7.4 1432.82    27.6 1432.83      36 1432.69    44.5 1432.44
    52.9 1432.53      72 1432.08    95.2 1431.35   103.7 1431.32   114.5 1431.02
   120.8 1430.95     129  1430.7   133.4 1430.65   141.7 1430.16   145.9 1429.67
   152.1 1427.58   154.4 1426.85   158.6 1426.44   161.8 1426.99   164.9  1427.7
     167 1428.19   171.3 1428.88   175.5 1429.07   221.7 1429.59   238.9 1429.89
   247.4 1430.12   251.6 1430.16   256.3 1430.07   275.2 1430.16     293 1430.63
#Mann= 4 ,-1,0
       0     .07       0   152.1    .045       0   164.9     .07       0
     210     .06       0
Bank Sta=152.1,164.9
XS Rating Curve= 0 ,0
Exp/Cntr(USF)=0,0
Exp/Cntr=0.3,0.1

Type RM Length L Ch R = 1 ,2058    ,163.2,163.2,163.2
XS GIS Cut Line= 2
2186143.91645147724596.1327723662186129.18450801724296.494707625
#Sta/Elev= 30
       0 1433.73      11 1432.64      27 1431.67      31 1431.23      35 1430.56
      47 1430.04      59 1429.06      63 1428.84    78.9 1428.13    95.1 1427.69
   111.1 1427.45   123.1 1427.54   127.1 1427.25   131.1 1425.64   135.1 1424.77
   139.1 1425.61   143.1 1427.17   147.1 1427.79   151.4 1427.73   155.1 1427.53
   171.2  1427.4   191.2 1427.12   195.2  1427.2   207.2 1427.78   215.2 1428.06
   235.2 1429.27   247.7 1429.65   259.3 1429.75   275.3 1429.52     300 1429.32
#Mann= 4 ,-1,0
       0     .07       0     130     .06       0   131.1    .045       0
   139.1     .06       0
#XS Ineff= 2 , 0
                          147.72         1429.16
Permanent Ineff=
       F       F
Bank Sta=131.1,139.1
XS Rating Curve= 0 ,0
Exp/Cntr(USF)=0,0
Exp/Cntr=0.3,0.1

Type RM Length L Ch R = 1 ,1894    ,177.2,177.2,177.2
XS GIS Cut Line= 2
2186325.65422487724562.5480664922186262.07702633724297.113262591
#Sta/Elev= 30
       0 1431.32     6.4 1430.97    30.2 1429.09    46.7 1427.89    58.8 1427.13
    67.2 1426.78      82 1426.55    87.8 1426.66    98.6 1426.52   108.3 1426.59
   120.7 1426.43   128.9 1426.51     133 1426.16   137.1 1425.34   141.81424.532
   145.4 1423.88   149.5 1424.03   151.7 1424.55   153.6 1424.99   157.7 1425.55
   161.6 1425.61     170 1425.55   178.2 1425.69   190.6 1426.16   194.7 1426.22
     203 1426.59   219.4 1426.79   231.7 1427.31   251.2  1427.9   272.9 1428.73
#Mann= 3 ,-1,0
       0     .06       0   141.8    .045       0   151.7     .06       0
Bank Sta=141.8,151.7
XS Rating Curve= 0 ,0
Exp/Cntr(USF)=0,0
Exp/Cntr=0.3,0.1

Type RM Length L Ch R = 1 ,1717    ,90.2,90.2,90.2
XS GIS Cut Line= 2
2186432.23250582724533.718825829 2186446.7148263724234.068592401
#Sta/Elev= 30
       0 1428.64    12.6 1428.34    20.6 1427.87    24.6 1427.48    34.8 1426.16
    40.6 1425.77    59.5 1425.77    76.6 1426.65   100.7 1427.12   114.2 1426.96
   128.7 1426.47   160.7 1425.78   164.7 1425.22   168.7 1423.58   172.7 1421.83
   176.2 1422.86   177.61423.534   180.8 1425.26   184.8  1426.2   188.8 1426.63
   200.8  1426.5   212.8 1426.69   224.8 1426.66   232.8 1426.85   240.8 1427.22
   248.8 1427.34   276.9 1428.36   288.9 1429.05   292.9 1429.52     300 1431.36
#Mann= 3 ,-1,0
       0     .06       0   168.7    .045       0   177.6     .06       0
Bank Sta=168.7,177.6
XS Rating Curve= 0 ,0
Exp/Cntr(USF)=0,0
Exp/Cntr=0.3,0.1

Type RM Length L Ch R = 1 ,1627    ,29.9,29.9,29.9
XS GIS Cut Line= 2
2186445.24040568724540.5648634242186585.94180533724279.360716572
#Sta/Elev= 30
       0 1428.69     6.2  1428.7    12.9 1428.54      22 1427.95    31.2 1426.43
    35.6 1425.98    39.9 1425.85    53.8 1425.65    76.5 1426.71    99.2 1426.34
   113.9 1425.69   125.7 1425.59   144.7 1424.99   149.4 1424.68   152.3 1424.14
   153.8  1423.8   158.2 1422.21   162.9 1420.91   164.1 1421.04   167.4 1422.07
     170 1423.58     172 1424.55   175.9 1425.22     181 1425.53   196.6 1425.81
   221.9 1426.52     231 1427.15   252.7 1427.49   291.1 1426.95   296.7 1427.17
#Mann= 6 ,-1,0
       0     .06       0      90     .07       0   158.2    .045       0
   167.4     .07       0     200     .06       0     230     .07       0
Bank Sta=158.2,167.4
XS Rating Curve= 0 ,0
Exp/Cntr(USF)=0,0
Exp/Cntr=0.3,0.1

Type RM Length L Ch R = 1 ,1597    ,90.3,90.3,90.3
XS GIS Cut Line= 2
2186477.02900495724544.538438333 2186617.7304046724283.334291481
#Sta/Elev= 30
       0 1427.92     8.4 1427.38      22 1425.87    25.5 1425.69    44.7 1425.64
    67.4 1426.46      72 1426.45   121.9 1425.29     131  1424.9   140.1 1424.69
   144.7 1423.68   149.2 1422.15   150.21421.922   152.4 1421.62   153.7 1421.56
   155.4 1421.99   161.3 1424.39   162.8 1424.79   166.9 1425.14   171.9 1425.33
     182 1425.44   199.7 1426.32   235.5 1427.13   242.8 1427.04   252.8 1427.14
   258.2 1426.71   262.8 1426.52     281 1426.53   285.5 1426.82   296.7 1427.82
#Mann= 4 ,-1,0
       0     .06       0      90     .07       0   150.2    .045       0
   155.4     .07       0
Bank Sta=150.2,155.4
XS Rating Curve= 0 ,0
Exp/Cntr(USF)=0,0
Exp/Cntr=0.3,0.1

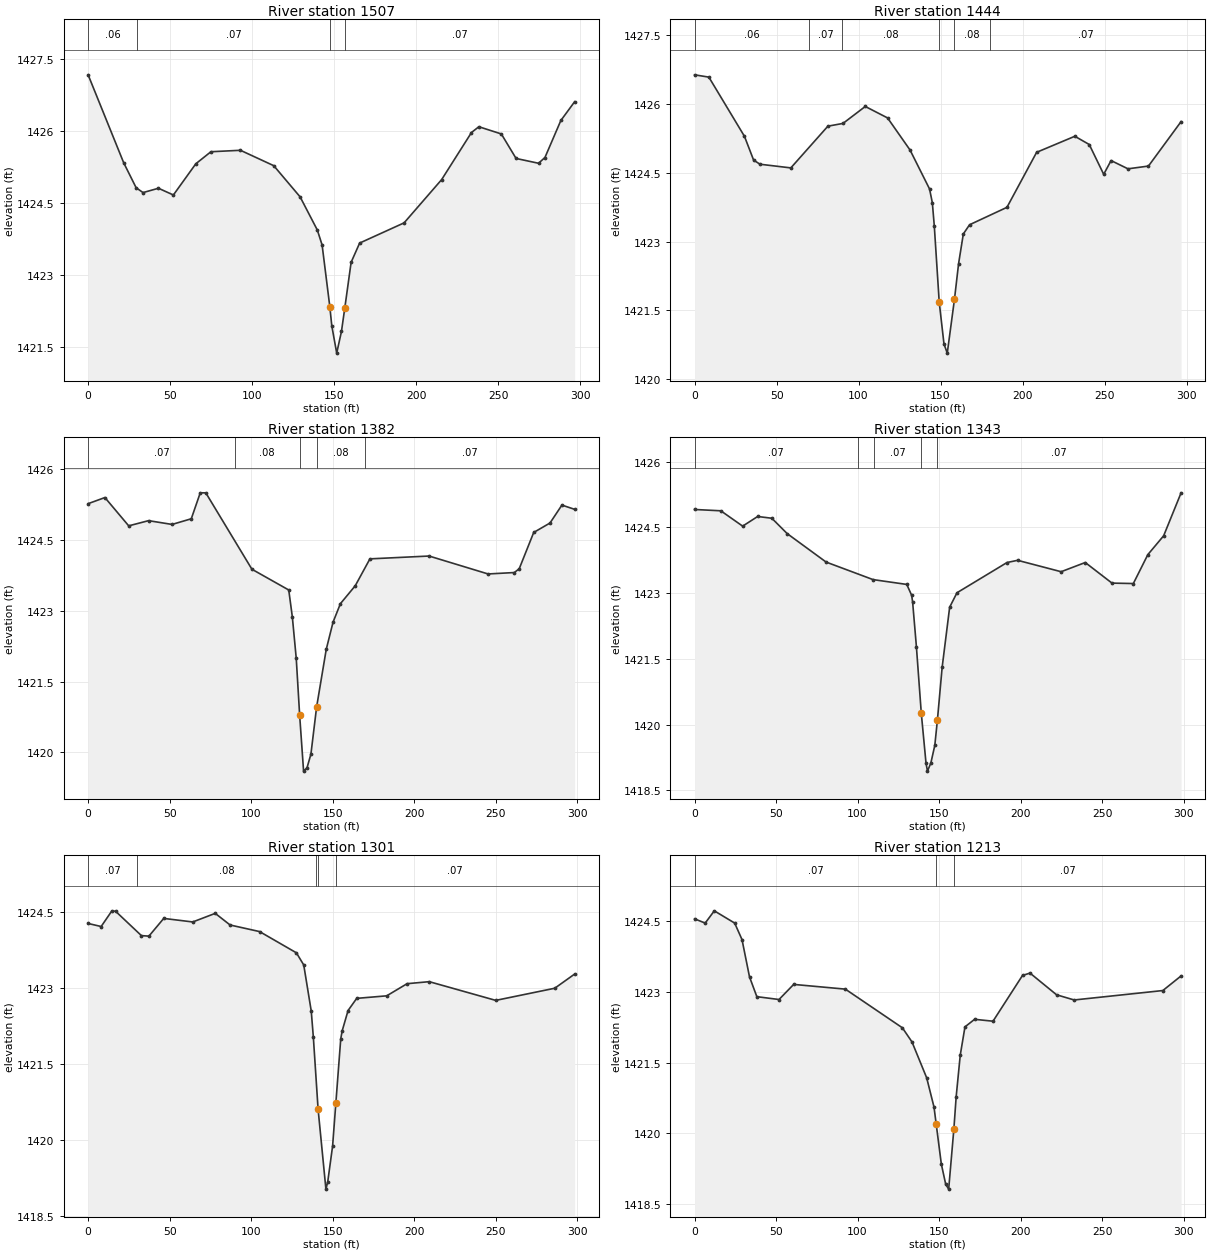
Type RM Length L Ch R = 1 ,1507    ,62.8,62.8,62.8
XS GIS Cut Line= 2
2186556.63548899724586.9839154642186697.33688863724325.779768612
#Sta/Elev= 30
       0 1427.17    21.7 1425.34    29.3 1424.82    33.5 1424.72    42.9 1424.81
      52 1424.67    65.7 1425.32    74.9 1425.57    92.9  1425.6   113.2 1425.28
   129.3 1424.63   139.8 1423.94   142.7 1423.63   147.41422.347   148.6 1421.95
   151.6 1421.38   154.5 1421.83   156.5 1422.31   160.4 1423.27   165.6 1423.67
   192.7 1424.09   215.6 1424.99   233.8 1425.97   238.3 1426.09     252 1425.94
     261 1425.43   274.7 1425.33   278.6 1425.45   288.3 1426.22   296.7 1426.61
#Mann= 4 ,-1,0
       0     .06       0      30     .07       0   147.4    .045       0
   156.5     .07       0
Bank Sta=147.4,156.5
XS Rating Curve= 0 ,0
Exp/Cntr(USF)=0,0
Exp/Cntr=0.3,0.1

Type RM Length L Ch R = 1 ,1444    ,61.5,61.5,61.5
XS GIS Cut Line= 2
 2186609.7464069 724620.831076582186750.44780655724359.626929728
#Sta/Elev= 30
       0 1426.64     8.7 1426.59    30.4  1425.3      36 1424.78    39.9 1424.69
    58.7 1424.61    81.3 1425.52    90.5 1425.58   104.1 1425.95   117.7  1425.7
   131.4    1425   143.3 1424.15     145 1423.85   146.2 1423.34   149.2 1421.68
   152.1 1420.77   154.1 1420.57   158.51421.746     161 1422.52   163.9 1423.17
   167.7 1423.37   190.5 1423.75   208.6 1424.95   231.9  1425.3   240.7 1425.12
   249.5 1424.47     254 1424.77   264.3 1424.59   276.8 1424.65   296.7 1425.62
#Mann= 6 ,-1,0
       0     .06       0      70     .07       0      90     .08       0
   149.2    .045       0   158.5     .08       0     180     .07       0
Bank Sta=149.2,158.5
XS Rating Curve= 0 ,0
Exp/Cntr(USF)=0,0
Exp/Cntr=0.3,0.1

Type RM Length L Ch R = 1 ,1382    ,39.3,39.3,39.3
XS GIS Cut Line= 2
2186671.32909143724637.9413030862186811.25122921724374.305302492
#Sta/Elev= 30
       0 1425.27    10.3  1425.4    24.9  1424.8    37.1 1424.91    51.5 1424.83
    63.3 1424.95    68.8  1425.5    72.2  1425.5   100.5 1423.88   123.1 1423.44
   125.3 1422.87   127.7 1421.99   129.8 1420.78   132.2  1419.6   134.3 1419.67
   136.7 1419.96   140.2 1420.96   146.1 1422.18   150.3 1422.76   154.8 1423.15
   163.9 1423.53   172.9  1424.1   209.2 1424.16   245.4 1423.78   261.5 1423.81
   264.5 1423.89   273.4 1424.66   283.4 1424.86   290.7 1425.24   298.5 1425.15
#Mann= 5 ,-1,0
       0     .07       0      90     .08       0   129.8    .045       0
   140.2     .08       0     170     .07       0
Bank Sta=129.8,140.2
XS Rating Curve= 0 ,0
Exp/Cntr(USF)=0,0
Exp/Cntr=0.3,0.1

Type RM Length L Ch R = 1 ,1343    ,42.4,42.4,42.4
XS GIS Cut Line= 2
2186702.32297572724663.3721825022186842.24511349724399.736181908
#Sta/Elev= 30
       0 1424.91    16.1 1424.88    29.5 1424.53    38.7 1424.75    47.4 1424.71
    56.8 1424.36    80.7 1423.71   109.5 1423.31   130.2  1423.2   133.2 1422.95
   133.8 1422.79   136.1 1421.78   139.1 1420.26     142 1419.12   142.9 1418.94
     145 1419.13   147.4 1419.53     149 1420.11   151.9 1421.31   156.5 1422.68
     161 1423.01   191.7  1423.7   198.2 1423.75   224.9 1423.49   239.7  1423.7
   256.1 1423.23   269.2 1423.22   278.1 1423.88   287.8 1424.31   298.5 1425.29
#Mann= 5 ,-1,0
       0     .07       0     100     .08       0     110     .07       0
   139.1    .045       0     149     .07       0
Bank Sta=139.1,149
XS Rating Curve= 0 ,0
Exp/Cntr(USF)=0,0
Exp/Cntr=0.3,0.1

Type RM Length L Ch R = 1 ,1301    ,87.6,87.6,87.6
XS GIS Cut Line= 2
2186738.27477404724686.0826027542186878.19691181 724422.44660216
#Sta/Elev= 30
       0 1424.28       8 1424.22    14.6 1424.53    16.9 1424.52    32.7 1424.04
    37.3 1424.03    46.4 1424.38    64.2 1424.31      78 1424.48    87.1 1424.25
   105.2 1424.12   127.8  1423.7   132.3 1423.46   136.9 1422.55   138.2 1422.03
   141.1 1420.61   145.9 1419.03     147 1419.17     150 1419.88     152 1420.73
     155    1422   155.9 1422.16   159.5 1422.56   164.8  1422.8   183.2 1422.85
   195.7 1423.09   209.3 1423.13   250.1 1422.76   286.3    1423   298.5 1423.28
#Mann= 5 ,-1,0
       0     .07       0      30     .08       0     140     .07       0
   141.1    .045       0     152     .07       0
Bank Sta=141.1,152
XS Rating Curve= 0 ,0
Exp/Cntr(USF)=0,0
Exp/Cntr=0.3,0.1

Type RM Length L Ch R = 1 ,1213    ,151.2,151.2,151.2
XS GIS Cut Line= 2
2186813.58307316 724730.922955952186953.50521094724467.286955356
#Sta/Elev= 30
       0 1424.55     6.5 1424.46    12.1 1424.72    24.6 1424.46    29.1 1424.11
    33.7 1423.32    38.2  1422.9    51.8 1422.84    60.8 1423.16    92.5 1423.06
   127.5 1422.24   133.4 1421.94   142.4 1421.18   146.9 1420.56   148.2 1420.21
   151.4 1419.35   154.1 1418.92   155.9 1418.82   159.1  1420.1   160.5 1420.78
     163 1421.66   165.9 1422.26   171.8 1422.42   183.1 1422.38   201.2 1423.35
   205.8  1423.4   222.1 1422.94   232.9 1422.83   287.3 1423.03   298.5 1423.34
#Mann= 3 ,-1,0
       0     .07       0   148.2    .045       0   159.1     .07       0
Bank Sta=148.2,159.1
XS Rating Curve= 0 ,0
Exp/Cntr(USF)=0,0
Exp/Cntr=0.3,0.1

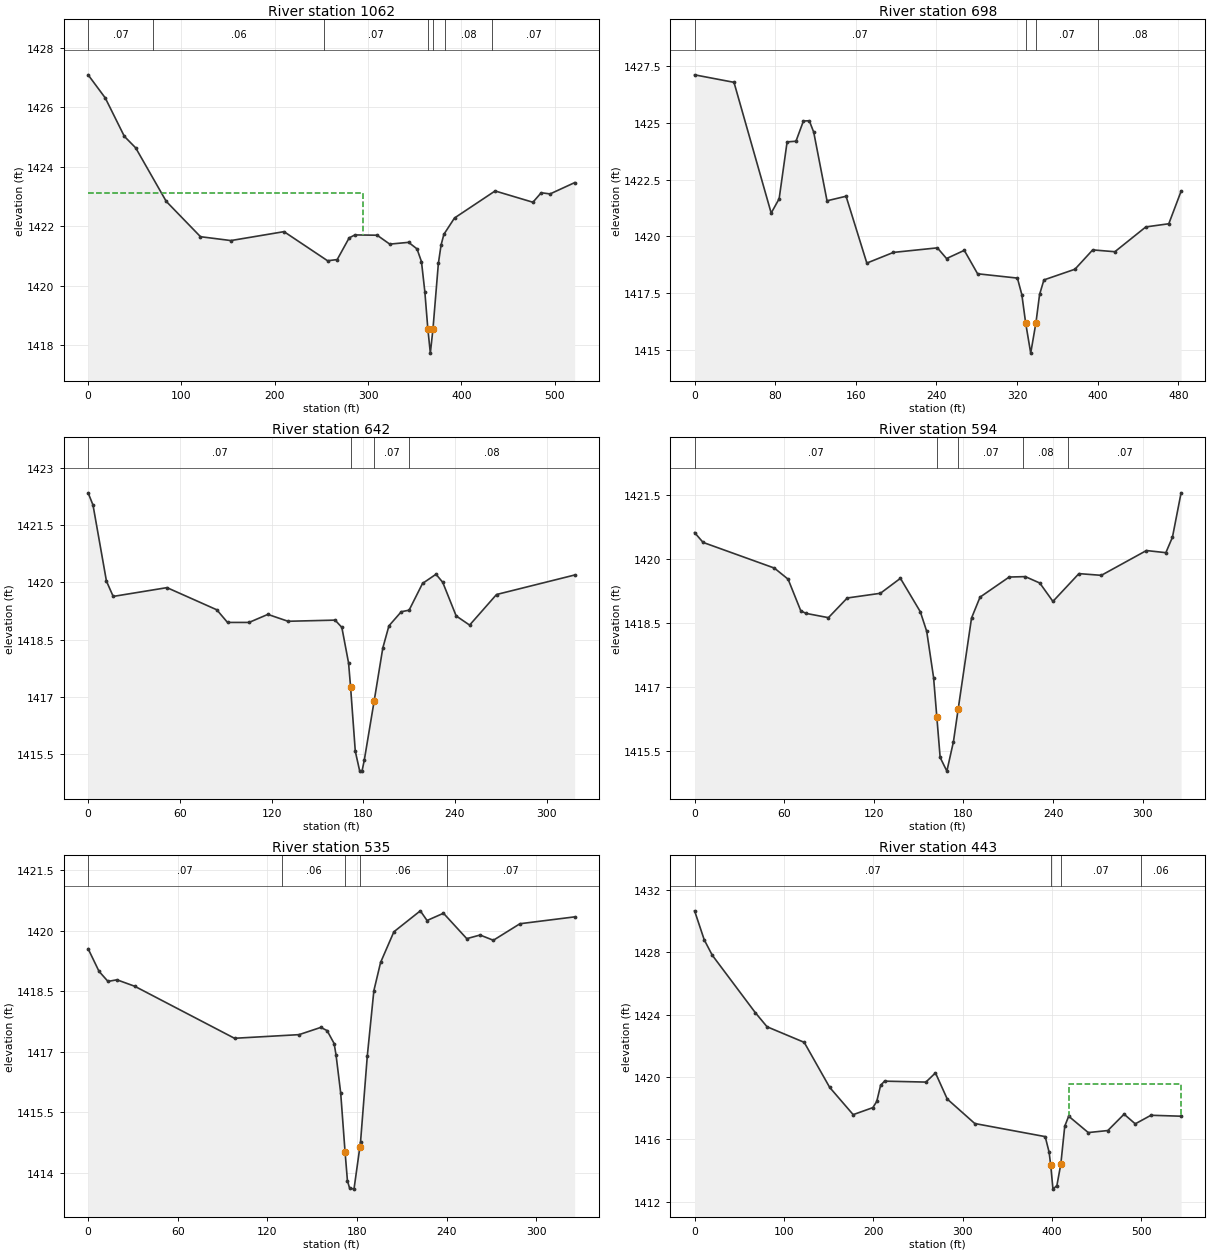
Type RM Length L Ch R = 1 ,1062    ,364.2,364.2,364.2
XS GIS Cut Line= 3
2186738.12251768724874.2644323662186907.68724002724840.245618326
2187095.82484081724547.057031373
#Sta/Elev= 30
       0  1427.1    18.4 1426.32    38.8 1425.03      51 1424.64    83.7 1422.84
   120.4 1421.65     153 1421.52   209.9 1421.82   256.6 1420.84   266.9 1420.88
   279.7 1421.61   285.9 1421.71   309.7  1421.7   323.2  1421.4   343.4 1421.46
   352.4 1421.24   357.2 1420.81   360.8  1419.8     3641418.554   366.7 1417.73
   369.5 1418.54   375.3 1420.75   378.2 1421.37   381.2 1421.73   392.6 1422.28
   436.1 1423.19   476.6 1422.81   485.5 1423.13     495 1423.09   521.3 1423.47
#Mann= 7 ,-1,0
       0     .07       0      70     .06       0  252.94     .07       0
     364    .045       0   369.5     .07       0  382.94     .08       0
  432.94     .07       0
#XS Ineff= 2 , 0
          294.76 1423.13
Permanent Ineff=
       F       F
Bank Sta=364,369.5
XS Rating Curve= 0 ,0
Exp/Cntr(USF)=0,0
Exp/Cntr=0.3,0.1

Type RM Length L Ch R = 1 ,698     ,55.8,55.8,55.8
XS GIS Cut Line= 2
2186748.60348343724893.705913359 2187187.9943623725093.510285517
#Sta/Elev= 30
       0 1427.11    39.1 1426.78      76 1421.03    83.9 1421.66    91.8 1424.16
   100.6 1424.19     108 1425.08   113.8 1425.09   118.2 1424.59   131.4 1421.57
   150.3 1421.77   170.9 1418.83   197.3  1419.3   240.9  1419.5     250 1419.03
   267.6 1419.39   280.8 1418.36   320.3 1418.17   324.7 1417.44   328.5 1416.19
   333.5 1414.87   338.7 1416.21   342.3 1417.45   346.6 1418.09   377.4 1418.56
     395 1419.41     417 1419.33   447.7 1420.42   470.5 1420.56   482.7 1421.99
#Mann= 4 ,-1,0
       0     .07       0   328.5    .045       0   338.7     .07       0
     400     .08       0
Bank Sta=328.5,338.7
XS Rating Curve= 0 ,0
Exp/Cntr(USF)=0,0
Exp/Cntr=0.3,0.1

Type RM Length L Ch R = 1 ,642     ,48.3,48.3,48.3
XS GIS Cut Line= 2
2186861.29212256725004.4095963412187150.56837592725137.126998292
#Sta/Elev= 30
       0 1422.34     3.2 1422.02      12 1420.03    16.4 1419.63    51.6 1419.86
    84.2 1419.28    91.2 1418.95   105.3 1418.95   117.6 1419.16   130.8 1418.98
   161.6 1419.01     166 1418.82   170.4 1417.89   171.7 1417.27   174.8 1415.58
   177.7 1415.06   179.2 1415.06   180.7 1415.35   187.11416.884   192.8 1418.28
   196.8 1418.86   204.9 1419.23     210 1419.27   218.8 1419.97   227.6 1420.21
     232    1420   240.8 1419.12   249.6 1418.88   267.2 1419.68   318.3 1420.19
#Mann= 4 ,-1,0
       0     .07       0   171.7    .045       0   187.1     .07       0
     210     .08       0
Bank Sta=171.7,187.1
XS Rating Curve= 0 ,0
Exp/Cntr(USF)=0,0
Exp/Cntr=0.3,0.1

Type RM Length L Ch R = 1 ,594     ,58.8,58.8,58.8
XS GIS Cut Line= 2
2186852.11924854725049.5965278212187145.43638026725191.279439529
#Sta/Elev= 30
       0 1420.61     5.7 1420.38    53.4 1419.78    62.6 1419.52    71.1 1418.78
    74.6 1418.72    89.6 1418.62   102.2 1419.08   124.4 1419.19   137.8 1419.54
   151.1 1418.76   155.4  1418.3     160 1417.22   162.21416.285   164.4 1415.35
   168.9 1415.03   173.3 1415.72   176.5 1416.49   185.4 1418.61   191.1  1419.1
   210.6 1419.57   221.4 1419.58   231.1 1419.43   239.9    1419   257.3 1419.65
   272.3 1419.61   302.5 1420.19   315.5 1420.14   319.9  1420.5   325.7 1421.54
#Mann= 5 ,-1,0
       0     .07       0   162.2    .045       0   176.5     .07       0
     220     .08       0     250     .07       0
Bank Sta=162.2,176.5
XS Rating Curve= 0 ,0
Exp/Cntr(USF)=0,0
Exp/Cntr=0.3,0.1

Type RM Length L Ch R = 1 ,535     ,91.6,91.6,91.6
XS GIS Cut Line= 2
2186831.88766824725103.7489690592187125.20479996725245.431880766
#Sta/Elev= 30
       0 1419.55     7.3 1418.99    13.3 1418.74    19.3 1418.78    31.2 1418.62
      98 1417.33   141.2 1417.42   155.8  1417.6     160 1417.52   164.7  1417.2
     166 1416.91   169.1 1415.97     172 1414.52   173.6  1413.8     175 1413.62
     178 1413.59   181.91414.627   182.4 1414.77   186.9 1416.89   191.3 1418.51
   195.8 1419.21   204.7 1419.97   222.4 1420.49   226.9 1420.25   237.9 1420.43
   253.5  1419.8   262.4 1419.89   271.3 1419.76   289.1 1420.17   325.7 1420.34
#Mann= 5 ,-1,0
       0     .07       0     130     .06       0     172    .045       0
   181.9     .06       0     240     .07       0
Bank Sta=172,181.9
XS Rating Curve= 0 ,0
Exp/Cntr(USF)=0,0
Exp/Cntr=0.3,0.1

Type RM Length L Ch R = 1 ,443     ,83.7,83.7,83.7
XS GIS Cut Line= 2
2186590.19620083725100.9135044942187086.99117738725323.885019001
#Sta/Elev= 30
       0 1430.67    10.8 1428.81    19.7 1427.83    67.9 1424.14    81.1 1423.23
   122.7 1422.23   151.2 1419.34   177.5 1417.59   199.5 1418.04   203.9 1418.44
   208.2 1419.47   212.6 1419.74   258.9 1419.68   269.6 1420.27   282.8 1418.59
   313.6 1417.02   392.4 1416.18   396.8 1415.18   398.61414.334   401.1 1412.81
   405.5 1413.04   409.9 1414.42   414.3 1416.85   418.7 1417.49   440.6 1416.44
   462.5 1416.57   480.7 1417.62   493.2    1417   510.8 1417.55   544.5 1417.49
#Mann= 4 ,-1,0
       0     .07       0   398.6    .045       0   409.9     .07       0
     500     .06       0
#XS Ineff= 2 , 0
                          419.15         1419.53
Permanent Ineff=
       F       F
Bank Sta=398.6,409.9
XS Rating Curve= 0 ,0
Exp/Cntr(USF)=0,0
Exp/Cntr=0.3,0.1

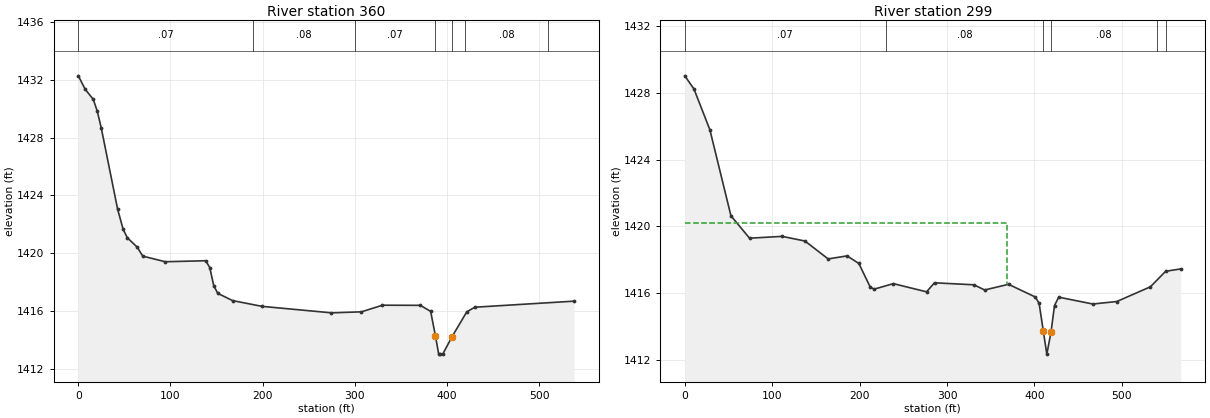
Type RM Length L Ch R = 1 ,360     ,61,61,61
XS GIS Cut Line= 2
2186577.34340298  725188.04762492187071.09687774725401.767087211
#Sta/Elev= 30
       0 1432.28     7.4 1431.35    16.2 1430.65    20.5 1429.84    24.9 1428.66
    42.6 1423.05    48.6 1421.65    53.2 1421.06    63.9 1420.41    69.9 1419.79
    94.3  1419.4   138.2 1419.47   142.6    1419   146.9 1417.75   151.3 1417.21
   167.3 1416.71   199.2 1416.31   274.7 1415.86   307.2 1415.93     330 1416.39
   371.1 1416.38   382.3 1415.96   387.5 1414.26     391 1413.01   392.4    1413
   395.4    1413   405.6 1414.22   421.5 1415.93   430.2 1416.25     538 1416.67
#Mann= 7 ,-1,0
       0     .07       0     190     .08       0     300     .07       0
   387.5    .045       0   405.6     .07       0     420     .08       0
     510     .07       0
Bank Sta=387.5,405.6
XS Rating Curve= 0 ,0
Exp/Cntr(USF)=0,0
Exp/Cntr=0.3,0.1

Type RM Length L Ch R = 1 ,299     ,176.9,176.9,176.9
XS GIS Cut Line= 2
2186546.69415839725232.7579351932187063.75199659725466.211372024
#Sta/Elev= 30
       0 1429.01    10.5 1428.22    28.7 1425.78    52.8 1420.63    74.1 1419.29
   111.3  1419.4   137.5 1419.12     164 1418.05   185.7 1418.23   199.1 1417.78
   212.3 1416.35   216.7 1416.24   238.6 1416.57   276.6 1416.08   285.7 1416.62
   330.8  1416.5   343.1 1416.19   370.4 1416.53     401 1415.77   405.4 1415.39
   410.2 1413.73   414.2 1412.35     419 1413.66     423 1415.26   427.8 1415.76
   466.8 1415.35   494.3  1415.5   532.7 1416.38   550.2 1417.31   567.3 1417.45
#Mann= 6 ,-1,0
       0     .07       0     230     .08       0   410.2    .045       0
     419     .08       0     540     .07       0     550     .08       0
#XS Ineff= 2 , 0
          368.11  1420.2
Permanent Ineff=
       F       F
Bank Sta=410.2,419
XS Rating Curve= 0 ,0
Exp/Cntr(USF)=0,0
Exp/Cntr=0.3,0.1