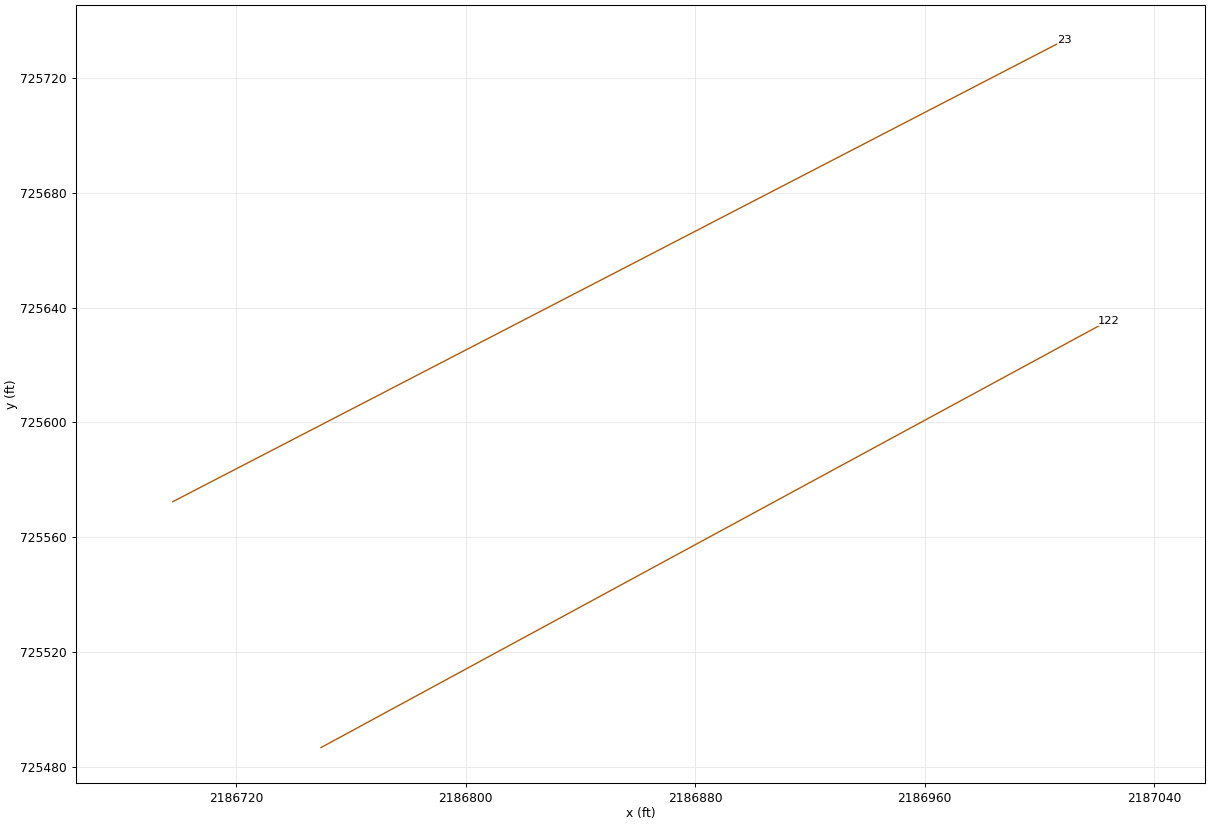
HEC-RAS study JAWBNRN.prj: JAWBNRN

--- JAWBNRN.g01 (geometry) --- (continued)

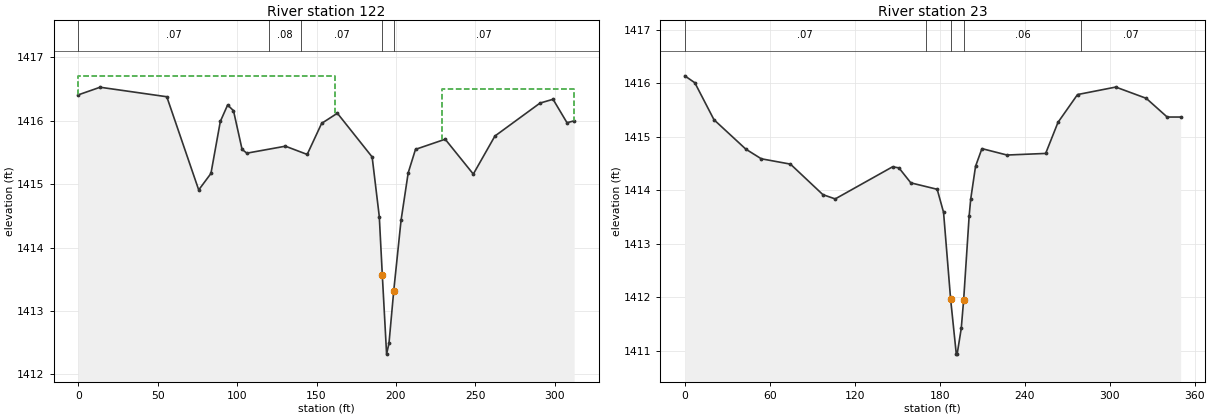
Type RM Length L Ch R = 1 ,122     ,98.2,98.2,98.2
XS GIS Cut Line= 2
2186749.53626816725486.6360125532187023.98920729725635.419926551
#Sta/Elev= 30
       0 1416.41    13.7 1416.53    55.7 1416.38    75.8 1414.91    83.5 1415.17
    89.4 1415.99      94 1416.25    97.7 1416.16   103.1 1415.55   106.1 1415.49
   130.4  1415.6   144.1 1415.47   153.2 1415.96   163.1 1416.12     185 1415.43
   189.5 1414.49   191.41413.569   194.1 1412.32   195.6 1412.49   198.6 1413.32
   203.2 1414.43   207.7 1415.18   212.3 1415.55     231 1415.71   248.7 1415.16
   262.3 1415.76   290.7 1416.28   298.9 1416.34   307.7 1415.97   312.2    1416
#Mann= 5 ,-1,0
       0     .07       0     120     .08       0     140     .07       0
   191.4    .045       0   198.6     .07       0
#XS Ineff= 2 , 0
          161.89 1416.71  228.93         1416.51
Permanent Ineff=
       F       F
Bank Sta=191.4,198.6
XS Rating Curve= 0 ,0
Exp/Cntr(USF)=0,0
Exp/Cntr=0.3,0.1

Type RM Length L Ch R = 1 ,23      ,,,
XS GIS Cut Line= 2
2186697.88624383 725572.356722892187008.80258613725733.286506693
#Sta/Elev= 30
       0 1416.14     7.1 1416.01    20.6 1415.32    43.1 1414.77      54 1414.59
    74.6 1414.49    97.5 1413.92   106.2 1413.84   146.7 1414.44   151.2 1414.42
   159.6 1414.14   178.2 1414.02   182.7 1413.59   187.71411.965   191.7 1410.94
   192.3 1410.94   195.2 1411.42   196.91411.957   200.8 1413.53   201.9 1413.84
   205.3 1414.45   209.8 1414.78   227.5 1414.66   254.8 1414.69   263.5 1415.27
   277.3 1415.79   304.3 1415.93   325.8 1415.72   340.6 1415.37350.0962 1415.37
#Mann= 5 ,-1,0
       0     .07       0     170     .06       0   187.7    .045       0
   196.9     .06       0     280     .07       0
Bank Sta=187.7,196.9
XS Rating Curve= 0 ,0
Exp/Cntr(USF)=0,0
Exp/Cntr=0.3,0.1
LCMann Table=0

Chan Stop Cuts=-1
Use User Specified Reach Order=0
Composite Channel Slope=5